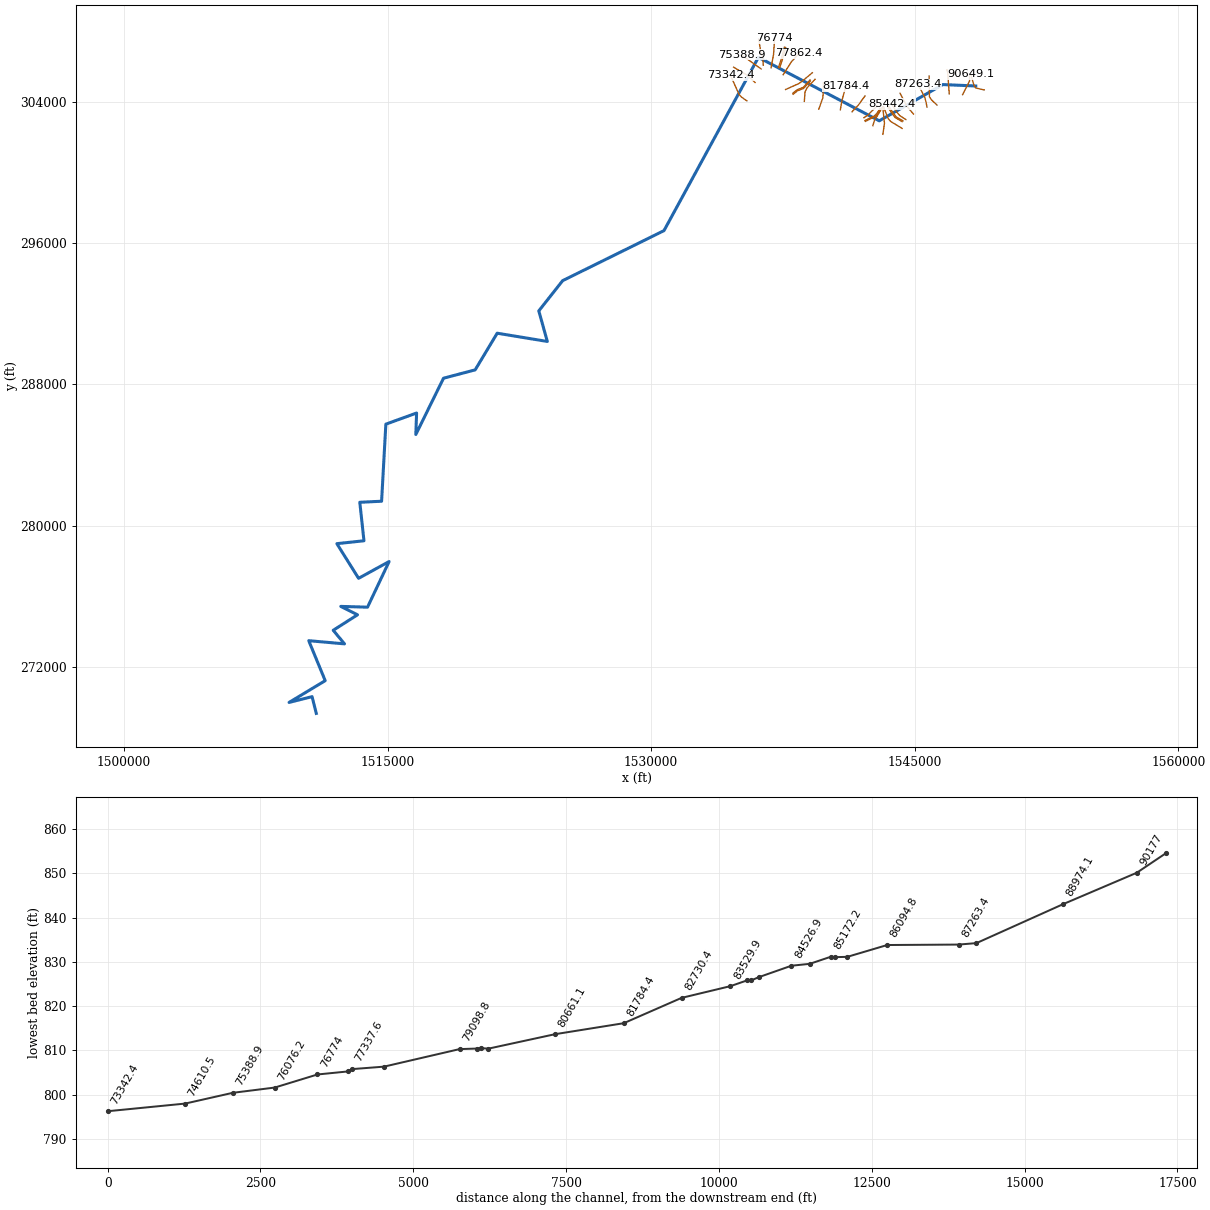
--- BNDSCR.prj (project) ---

Proj Title=BNDSCR
Current Plan=p01
Default Exp/Contr=0,0
English Units
Geom File=g01
Flow File=f01
Plan File=p01
BEGIN DESCRIPTION:
END DESCRIPTION:
DSS Export Rating Curves= 0
DSS Export Rating Curve Sorted= 0
DSS Export Volume Flow Curves= 0
DXF OffsetX= 0
DXF OffsetY= 0
DXF ScaleX= 0
DXF ScaleY= 0

--- BNDSCR.p01 (plan) ---

Plan Title=Floodplain
Program Version=4.00
Geom File=g01
Flow File=f01
K Sum by GR=0
Std Step Tol=0.01
Critical Tol=0.01
Num of Std Step Trials=20
Max Error Tol=0.3
Flow Tol Ratio=0.001
Split Flow NTrial=30
Split Flow Tol=0.02
Split Flow Ratio=0.02
Log Output Level=0
Friction Slope Method=1
Unsteady Friction Slope Method=2
Unsteady Bridges Friction Slope Method=1
Global Log Level=0
CheckData=False
Run HTab=0
Run UNet=0
Run PostProcess=0
UNET Theta=0
UNET Theta Warmup=0
UNET ZTol=0
UNET ZSATol=0
UNET MxIter=0
UNET MaxInSteps=0
UNET DtIC=0
UNET DtMin=0
UNET MaxCRTS=0
UNET WFStab=0
UNET SFStab=0
UNET WFX=0
UNET SFX=0
UNET DSS MLevel=0
UNET DZMax Abort=0
UNET Convert EG Bridges=0
UNET Use Existing IB Tables=0
UNET Froude Limit=0
UNET Froude Power=0
Write IC File=0
Echo Input=False
Echo Output=False
Write Detailed=0

--- BNDSCR.f01 (steady flow) ---

Flow Title=NFF Regression Equation
Program Version=4.10
Number of Profiles= 1
Profile Names=P100yr
River Rch & RM=BNDSCR,Main            ,90649.1
1065.039
River Rch & RM=BNDSCR,Main            ,90177
1171.546
River Rch & RM=BNDSCR,Main            ,87554.6
1249.823
River Rch & RM=BNDSCR,Main            ,87263.4
1360.768
River Rch & RM=BNDSCR,Main            ,84827.6
1401.348
River Rch & RM=BNDSCR,Main            ,84526.9
1658.371
River Rch & RM=BNDSCR,Main            ,83529.9
 1751.16
River Rch & RM=BNDSCR,Main            ,81784.4
1853.731
River Rch & RM=BNDSCR,Main            ,79568.3
 1930.18
River Rch & RM=BNDSCR,Main            ,77337.6
2069.419
River Rch & RM=BNDSCR,Main            ,76774
2281.958
River Rch & RM=BNDSCR,Main            ,75388.9
 2394.22
River Rch & RM=BNDSCR,Main            ,74610.5
2477.725
River Rch & RM=BNDSCR,Main            ,70182.7
2625.846
River Rch & RM=BNDSCR,Main            ,64670.7
2803.758
River Rch & RM=BNDSCR,Main            ,62187.4
3027.943
River Rch & RM=BNDSCR,Main            ,57647.6
3193.549
River Rch & RM=BNDSCR,Main            ,49790.8
3425.894
River Rch & RM=BNDSCR,Main            ,49449.8
3903.159
River Rch & RM=BNDSCR,Main            ,44829.7
4024.957
River Rch & RM=BNDSCR,Main            ,44487.7
4606.477
River Rch & RM=BNDSCR,Main            ,37173.5
4705.621
River Rch & RM=BNDSCR,Main            ,36260.6
4947.418
River Rch & RM=BNDSCR,Main            ,25475.7
5121.348
River Rch & RM=BNDSCR,Main            ,24414.4
5406.363
River Rch & RM=BNDSCR,Main            ,11264.6
5586.503
River Rch & RM=BNDSCR,Main            ,10651.7
7000.779
River Rch & RM=BNDSCR,Main            ,829
7083.922
River Rch & RM=BNDSCR,Main            ,206.1
  7084.7
Boundary for River Rch & Prof#=BNDSCR,Main            , 1
Up Type= 0
Dn Type= 3
Dn Slope=0.0003
DSS Import GetInterval= 0
DSS Import GetPeak= 0
DSS Import FillOption= 0

--- BNDSCR.g01 (geometry) ---

Geom Title=USGS 10m DEM
Program Version=4.10

River Reach=BNDSCR          ,Main
Reach XY= 30
     1548471.885      304901.673     1546599.631       304981.63
     1542981.821       302930.02     1536102.581      306523.661
     1530730.552      296709.009     1524963.508      293875.308
     1523605.869      292163.069     1524091.112      290431.731
     1521238.247      290899.179     1519985.426      288822.899
     1518184.211      288349.809     1516607.822      285162.309
     1516651.225      286377.587     1514902.093      285748.246
     1514659.906      281382.795     1513419.454      281322.899
     1513656.433      279143.212     1512113.899      278979.149
     1513350.878      277016.475     1515086.902      277966.389
     1513860.179      275382.418     1512335.874      275425.821
     1513289.867      274950.994     1511907.922       274073.39
     1512548.439      273304.588     1510513.717      273483.755
     1511451.217      271219.171     1509393.578      269985.838
     1510701.911      270313.616     1510943.497      269367.026

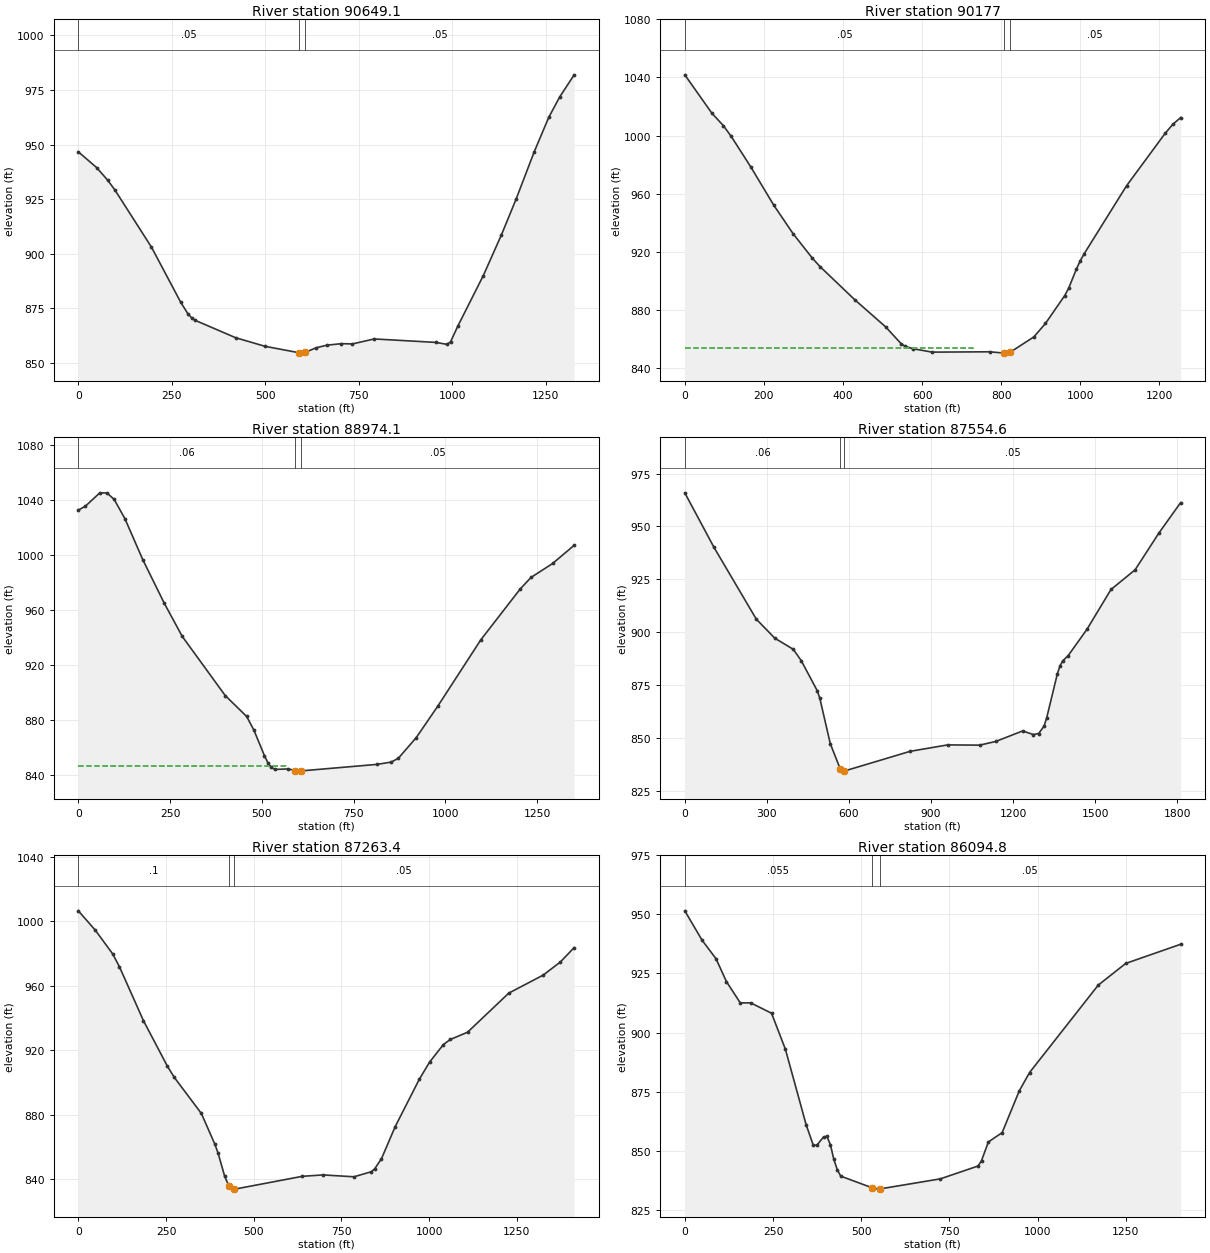
Type RM Length L Ch R = 1 ,90649.1 ,495.8,472,445.7
XS GIS Cut Line= 4
     1548953.826      304679.213     1548466.847      304788.588
     1548365.284      304955.254     1548188.201      305562.025
#Sta/Elev= 30
       0   946.7    48.9   939.5    78.3  933.76    97.9  929.22   195.7  903.03
     274  877.76   293.6   872.4   303.4   870.6   313.2  869.47   420.8  861.55
   499.1  857.63   590.7  854.66   596.7  854.49  607.09 854.858   635.7  856.91
     665  858.14     704  858.82   733.2   858.7   791.5  860.99   956.8   859.4
     986  858.51   995.7  859.66  1015.2  866.87  1083.3  889.99  1131.9  908.69
  1170.8  924.92  1219.4  946.65  1258.3  962.45  1287.5  971.78  1326.4  981.98
#Mann= 3 , 0 , 0
       0     .05       0   590.7    .045       0  607.09     .05       0
Bank Sta=590.7,607.09
XS Rating Curve= 0 ,0
Exp/Cntr=0.3,0.1

Type RM Length L Ch R = 1 ,90177   ,1191.1,1202.9,1214.2
XS GIS Cut Line= 4
     1547723.097      304411.606     1548068.409      305080.254
     1548117.888      305179.213     1548117.888      305569.838
#Sta/Elev= 30
       0 1041.83    68.4 1015.43    97.7 1006.78   117.3  999.46   166.2  978.67
   224.8  952.11   273.6  932.49   322.5  915.54   342.1   909.7     430  886.85
   508.2  868.13   547.3  856.53   557.1  854.88   576.6  853.17   625.5  850.81
     771  851.04   806.9  850.15   807.9  850.12   821.9  850.58   882.7   861.3
     912  870.54   960.8   889.8   970.6  894.79   990.1  907.91   999.9   913.7
  1009.7  918.48  1117.1  965.41  1214.8 1001.58  1234.3 1007.79  1253.8 1012.39
#Mann= 3 , 0 , 0
       0     .05       0   806.9    .045       0   821.9     .05       0
#XS Ineff= 2 , 0
          728.18  853.76
Permanent Ineff=
       F       F
Bank Sta=806.9,821.9
XS Rating Curve= 0 ,0
Exp/Cntr=0.3,0.1

Type RM Length L Ch R = 1 ,88974.1 ,1407.6,1419.6,1431.1
XS GIS Cut Line= 4
     1546964.763      304459.942     1546923.444      304956.122
     1546915.631      305114.977     1546866.152      305807.685
#Sta/Elev= 30
       0 1032.65    19.5 1035.58    58.6 1045.22    78.1  1045.1    97.6 1040.48
   126.9 1026.47   175.7  996.65   234.3  964.97   283.1  940.97   400.3  897.97
   458.8  882.75   478.4  872.92   507.2  854.32   516.6  849.16     526  845.77
   535.3  844.27   572.7  844.64   591.6  843.42   600.8  843.04   606.6  843.19
   813.4  847.92   852.6   849.6   872.1  852.34     921  867.39   979.7  890.23
  1097.1  938.49  1204.7  975.48    1234  983.78  1292.7  993.88  1351.4  1007.1
#Mann= 3 , 0 , 0
       0     .06       0   591.6    .045       0   606.6     .05       0
#XS Ineff= 2 , 0
          567.21   846.8
Permanent Ineff=
       F       F
Bank Sta=591.6,606.6
XS Rating Curve= 0 ,0
Exp/Cntr=0.3,0.1

Type RM Length L Ch R = 1 ,87554.6 ,298.3,291.2,284.1
XS GIS Cut Line= 4
     1546263.722      303822.442     1545935.597      304137.546
     1545836.638      304291.192     1545814.937      305465.671
#Sta/Elev= 30
       0  965.91   106.5  940.15   261.3  906.15   329.1  897.12   396.8  891.85
   425.9  886.44   483.8  872.36   493.4  868.76   531.9  847.19     568  835.33
     580  834.23     583  834.27   823.7   843.6   960.7  846.64  1078.2  846.53
  1136.9  848.28  1234.8  853.24    1274  851.55  1293.5  852.03  1313.1  855.51
  1322.9  859.48  1362.1  880.41  1371.9  884.15  1381.6  886.44  1401.2  888.86
  1469.8  901.28  1557.8  920.17    1646  929.48    1734  947.08  1812.4  961.27
#Mann= 3 , 0 , 0
       0     .06       0     568    .045       0     583     .05       0
Bank Sta=568,583
XS Rating Curve= 0 ,0
Exp/Cntr=0.3,0.1

Type RM Length L Ch R = 1 ,87263.4 ,1158.6,1168.6,1178.1
XS GIS Cut Line= 4
     1545700.354      303701.782     1545637.029      304007.887
     1545574.529      304247.471     1545186.465      305007.338
#Sta/Elev= 30
       0 1006.61    48.8  994.49    97.7  979.95   117.2   971.9   185.6  938.46
     254  910.13   273.5  903.27   350.7  880.86   388.8  861.97   398.3  856.31
   417.3  841.79   429.8  835.57   444.8  833.93   445.9   833.9   638.6  841.85
   697.5  842.72   785.8  841.56   834.8  844.68   844.6  846.45   864.2   852.8
   903.4  872.76   972.1  902.14  1001.5  912.79  1040.7  923.64  1060.4  926.78
  1109.4  931.26  1227.1  955.55  1325.2  966.73  1374.2  974.88  1413.4  983.82
#Mann= 3 , 0 , 0
       0      .1       0   429.8    .045       0   444.8     .05       0
Bank Sta=429.8,444.8
XS Rating Curve= 0 ,0
Exp/Cntr=0.3,0.1

Type RM Length L Ch R = 1 ,86094.8 ,651.6,652.4,652.8
XS GIS Cut Line= 4
     1544925.614      303316.799     1544667.801      303613.674
     1544550.614      303756.904     1544165.197      304488.674
#Sta/Elev= 30
       0   951.5    49.2  939.03    88.5  931.24     118  921.58   157.3  912.55
   186.8  912.58   245.8   908.2   285.1  892.98     344     861   363.7  852.56
   373.5  852.26   393.2  855.85   402.9  856.09   412.7  852.58   422.4  846.39
   432.2  842.01   441.9   839.3   529.6  834.44     549   833.8   552.4  833.87
   724.2  838.14   831.2  843.58     841  845.86   860.4  853.75   899.4  857.69
     948  875.36   977.2  883.12  1171.8  920.08  1249.6  929.25  1405.3  937.35
#Mann= 3 , 0 , 0
       0    .055       0   529.6    .045       0   552.4     .05       0
Bank Sta=529.6,552.4
XS Rating Curve= 0 ,0
Exp/Cntr=0.3,0.1

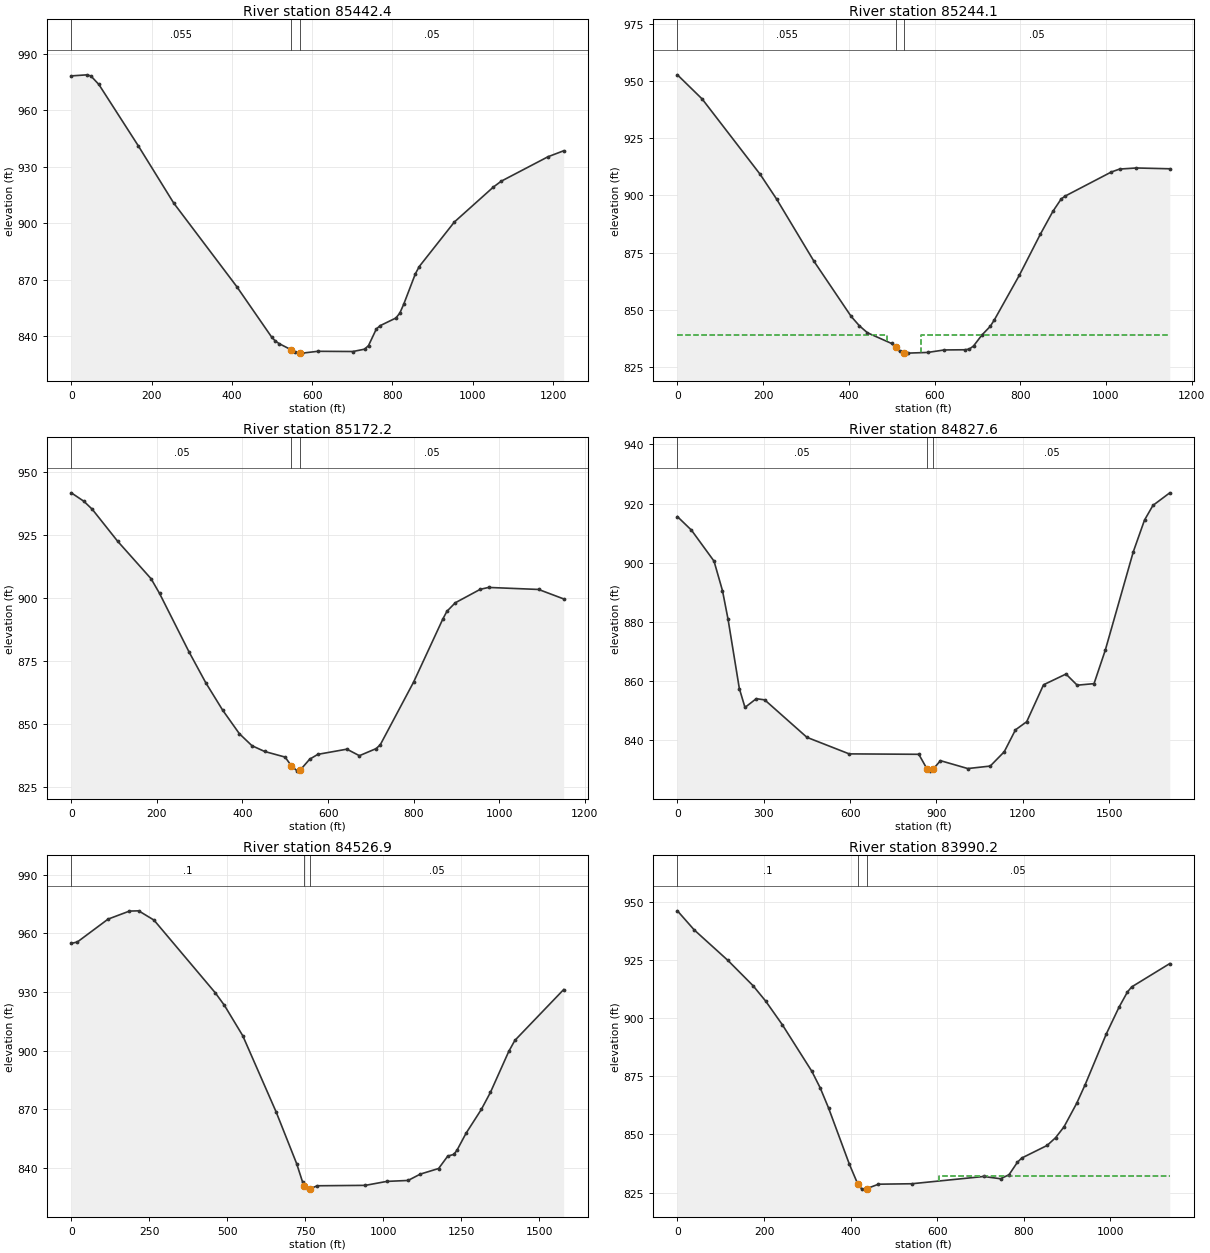
Type RM Length L Ch R = 1 ,85442.4 ,198.6,198.3,198
XS GIS Cut Line= 4
     1544500.267      302997.355     1544153.044      303219.577
       1544021.1      303372.355      1543677.35      303879.299
#Sta/Elev= 30
       0  978.14    39.3  978.71    49.1  978.06    68.7   973.6   166.9  941.07
   255.2   910.7   412.2  866.42   498.8  839.75   508.4  837.53     518  836.16
   546.8     833   556.4  831.74   570.6  831.14   575.7  831.13   614.1   832.1
   701.6  831.99   730.8  833.23   740.5  835.15     760  843.96   769.7  845.72
   808.6  849.74   818.3   852.3     828  856.96   857.2  873.19   866.9  877.06
   954.4  900.67  1051.6  919.21  1071.1   922.3  1187.7  935.28  1226.6  938.43
#Mann= 3 , 0 , 0
       0    .055       0   546.8    .045       0   570.6     .05       0
Bank Sta=546.8,570.6
XS Rating Curve= 0 ,0
Exp/Cntr=0.3,0.1

Type RM Length L Ch R = 1 ,85244.1 ,71.9,71.9,72
XS GIS Cut Line= 4
      1544329.26      302926.174      1543954.26      303144.924
     1543857.906      303259.508     1543534.989      303723.049
#Sta/Elev= 30
       0  952.66    57.9  942.07     193   909.2   231.5  898.35   318.4  871.26
   405.2  847.15   424.5  843.02   443.5  839.94   499.6  835.29     509  833.71
   518.4  831.85   527.9  831.11   537.1  831.06   583.8  831.36   622.8  832.45
   671.5  832.53   681.2  832.85     691   834.2   710.5  838.99     730  842.78
   739.7  845.66   798.1  865.19   846.8  883.02   876.1  893.02   895.5  898.44
   905.3  899.74  1012.4   910.2  1031.9  911.49  1070.9  911.96  1148.8  911.61
#Mann= 3 , 0 , 0
       0    .055       0     509    .045       0   527.9     .05       0
#XS Ineff= 2 , 0
          489.82  839.17  567.92          839.04
Permanent Ineff=
       F       F
Bank Sta=509,527.9
XS Rating Curve= 0 ,0
Exp/Cntr=0.3,0.1

Type RM Length L Ch R = 1 ,85172.2 ,344.2,344.6,344.9
XS GIS Cut Line= 4
     1544279.781      302884.508     1543889.156       303111.07
     1543790.197      303228.258     1543482.906      303678.779
#Sta/Elev= 30
       0  941.65    29.4   938.3    49.1   935.1     108  922.49   186.5  907.52
   206.2  901.71   274.9  878.55   314.1  866.27   353.4  855.43   392.7  846.01
   422.1  841.25   451.6  838.96   499.5  836.73  514.16833.2825   528.3  831.15
   534.2  831.45     557   835.9   576.2  837.82   643.9  839.87   673.1  837.28
   712.1  840.08   721.8  841.59   799.7  866.49   867.9   891.5   877.6  894.62
   897.1  897.99   955.5  903.34     975  904.09  1091.9  903.28  1150.3  899.53
#Mann= 3 , 0 , 0
       0     .05       0  514.16    .045       0   534.2     .05       0
Bank Sta=514.16,534.2
XS Rating Curve= 0 ,0
Exp/Cntr=0.3,0.1

Type RM Length L Ch R = 1 ,84827.6 ,314.2,300.6,286.9
XS GIS Cut Line= 4
     1544281.517      302497.355     1543621.794      302900.133
     1543486.378      303056.383     1543219.017      303736.938
#Sta/Elev= 30
       0  915.59    48.9     911   127.2  900.54   156.6  890.56   176.1  880.81
   215.2  857.46   234.8  851.08     274  854.04   303.3  853.64   450.1  840.97
   596.8  835.38   838.8  835.24   866.9  830.37   876.3  829.55  888.28830.1707
   913.9  833.09    1009  830.42    1087  831.26  1135.7   836.1  1174.7  843.51
  1213.7  846.25  1272.2  858.74  1350.2  862.37  1389.2   858.6  1447.7  859.13
  1486.7  870.41  1584.2  903.73  1623.2  914.44  1652.4  919.38  1710.9  923.63
#Mann= 3 , 0 , 0
       0     .05       0   866.9    .045       0  888.28     .05       0
Bank Sta=866.9,888.28
XS Rating Curve= 0 ,0
Exp/Cntr=0.3,0.1

Type RM Length L Ch R = 1 ,84526.9 ,552.2,536.7,520.8
XS GIS Cut Line= 4
     1543187.767      302164.022     1543278.044      302785.549
     1543253.739      303000.827      1543177.35      303729.994
#Sta/Elev= 30
       0   954.8    19.6  955.57   117.8  967.24   186.4  971.36   215.9  971.49
     265  966.75   461.2   929.6   490.7  923.14   549.5  907.59   656.3  868.67
   722.2  842.16   741.1  832.79   747.1830.9166   759.9  829.12   765.1  829.29
   788.2  830.84   942.4  831.05  1010.9  833.07  1079.3  833.56  1118.4   836.8
  1177.1  839.67  1206.4  846.02  1225.9  846.89  1235.7  848.94    1265   857.7
  1313.9  869.86  1343.2  878.63  1401.9  899.57  1421.4  905.19  1577.8  931.21
#Mann= 3 , 0 , 0
       0      .1       0   747.1    .045       0   765.1     .05       0
Bank Sta=747.1,765.1
XS Rating Curve= 0 ,0
Exp/Cntr=0.3,0.1

Type RM Length L Ch R = 1 ,83990.2 ,137.2,121.3,106.3
XS GIS Cut Line= 4
     1542618.322      302653.605       1542708.6      302960.897
     1542835.336      303153.605     1543135.683      303657.077
#Sta/Elev= 30
       0   946.1    38.8   937.9   116.5  924.82   174.7  913.93   203.8  907.33
   242.6  897.08   310.6  877.11   329.9  869.98   349.1  861.38   397.2  837.21
   416.4  828.78     426  826.52   436.9  826.71   464.4  828.64   541.3  828.83
   707.3  831.95   746.3  830.98   765.9  832.71   785.4  838.09   795.2  839.87
   853.8  845.28   873.4  848.61   892.9  853.28   922.2  863.41   941.8  871.43
   990.6  893.22  1019.9  904.67  1039.5  911.26  1049.2  913.41  1137.2  923.44
#Mann= 3 , 0 , 0
       0      .1       0   416.4    .045       0   436.9     .05       0
#XS Ineff= 2 , 0
                          605.24          832.13
Permanent Ineff=
       F       F
Bank Sta=416.4,436.9
XS Rating Curve= 0 ,0
Exp/Cntr=0.3,0.1

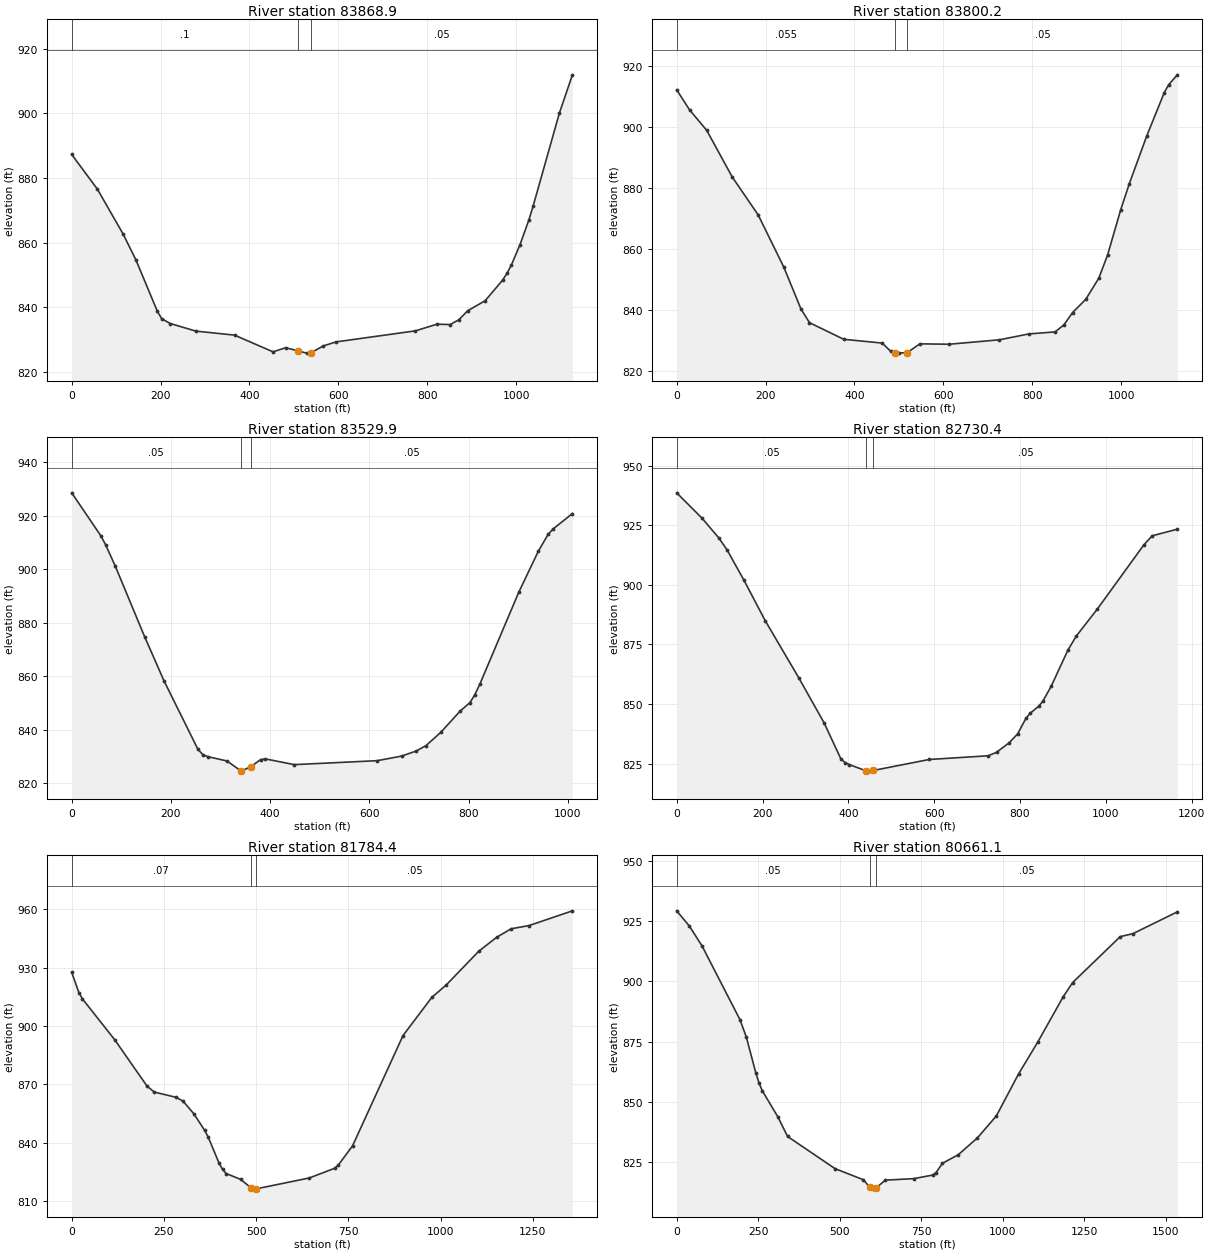
Type RM Length L Ch R = 1 ,83868.9 ,71.4,68.7,64.7
XS GIS Cut Line= 5
     1542199.919      302897.963     1542603.565      303103.692
     1542718.149      303146.661     1542870.492      303287.286
      1543056.69      303576.348
#Sta/Elev= 30
       0  887.27    57.8  876.53   115.7  862.64   144.6   854.6   192.8  838.72
   202.4  836.46   221.7  834.96   279.5  832.61   366.3  831.37     453   826.2
   481.3  827.47   509.5  826.49   528.4   825.8   538.8  825.95     566  828.02
   594.3  829.26   773.3  832.69     822  834.76   851.5  834.64   871.2  836.13
   890.8   838.9   930.1     842   969.4  848.36   979.2  850.46   989.1  853.02
  1008.7  859.35  1028.4  866.93  1038.2   871.3  1097.1     900  1126.6   911.9
#Mann= 3 , 0 , 0
       0      .1       0   509.5    .045       0   538.8     .05       0
Bank Sta=509.5,538.8
XS Rating Curve= 0 ,0
Exp/Cntr=0.3,0.1

Type RM Length L Ch R = 1 ,83800.2 ,254.6,270.3,285.7
XS GIS Cut Line= 5
     1542163.027      302941.365     1542566.673      303147.095
     1542681.256      303190.063       1542833.6      303330.688
     1543019.798      303619.751
#Sta/Elev= 30
       0  912.25    28.9  905.68    67.5  898.96   125.3  883.55   183.2  871.21
     241  854.04   279.5  840.33   298.8   835.8   375.9  830.34   462.5   829.1
   481.3  826.41   490.7  825.82   500.1   825.8   518.9  825.99   547.2  828.85
   613.1  828.72   726.2  830.18   792.6  832.11   851.5  832.77   871.2  835.08
   890.8  839.13   920.3  843.45   949.8  850.42   969.4  857.97   998.9  872.81
  1018.5  881.48  1057.8  897.18  1097.1  911.36  1106.9  913.93  1126.6  917.17
#Mann= 3 , 0 , 0
       0    .055       0   490.7    .045       0   518.9     .05       0
Bank Sta=490.7,518.9
XS Rating Curve= 0 ,0
Exp/Cntr=0.3,0.1

Type RM Length L Ch R = 1 ,83529.9 ,800.3,799.5,797.2
XS GIS Cut Line= 4
     1542112.441      303104.582     1542362.441      303276.457
     1542445.775      303370.207     1542862.441      303773.852
#Sta/Elev= 30
       0  928.58    58.7  912.52    68.5   909.1    88.1  901.04   146.8  874.83
   185.9  858.31   254.4  832.64   264.2  830.68     274  829.94     313   828.3
  340.92824.6102     342  824.51   361.3  826.24   380.6   828.8   390.2  829.08
   448.5  826.94   615.6  828.42   664.8  830.14   694.3  832.04     714  834.07
   743.5  838.99   782.8  846.98   802.4  850.13   812.3   853.1   822.1  856.93
   900.8  891.42   940.1  906.71   959.8  913.02   969.6  915.02  1008.9  920.83
#Mann= 3 , 0 , 0
       0     .05       0  340.92    .045       0   361.3     .05       0
Bank Sta=340.92,361.3
XS Rating Curve= 0 ,0
Exp/Cntr=0.3,0.1

Type RM Length L Ch R = 1 ,82730.4 ,932.2,946,959.7
XS GIS Cut Line= 4
     1541432.754      303437.915     1541635.879      303664.477
     1541789.525      303815.519     1542169.733      304338.957
#Sta/Elev= 30
       0  938.62    58.9  928.01    98.2  919.69   117.8  914.55     157  901.87
   206.1  885.04   284.7  860.94   343.5   842.1   382.6  826.99   392.4  825.45
   402.2   824.6   441.4  821.98   451.2  821.86   458.5  822.16   588.4  826.74
   725.6   828.3   745.2  829.74   774.6  833.74   794.2  837.42   813.8  844.02
   823.6  846.14   843.2  849.04     853  851.14   872.6  857.46   911.8  872.72
   931.4   878.6   980.4  889.92  1088.3  916.74  1107.9  920.59  1166.7  923.38
#Mann= 3 , 0 , 0
       0     .05       0   441.4    .045       0   458.5     .05       0
Bank Sta=441.4,458.5
XS Rating Curve= 0 ,0
Exp/Cntr=0.3,0.1

Type RM Length L Ch R = 1 ,81784.4 ,1127.2,1123.3,1118.8
XS GIS Cut Line= 4
     1540766.087      303552.498     1540828.587      303917.082
     1540865.045       304109.79     1541075.983      304872.811
#Sta/Elev= 30
       0  927.56    19.5  917.17    29.2   913.9   116.8  892.88   204.4  869.05
   223.9  866.04   282.3  863.36   301.8  861.43     331  854.89   360.2  846.46
   369.9  842.98   399.3  829.61   409.1  826.26   418.9  824.14   458.2  821.15
   485.9  816.85   497.4  816.14   500.9  816.31   644.2  821.87   712.6  826.83
   722.4  828.37   761.5  838.38   898.3  895.06   976.5  914.71  1015.6   921.1
  1103.6   938.4  1152.4  945.62  1191.5  949.96  1240.4  951.63  1357.7  959.19
#Mann= 3 , 0 , 0
       0     .07       0   485.9    .045       0   500.9     .05       0
Bank Sta=485.9,500.9
XS Rating Curve= 0 ,0
Exp/Cntr=0.3,0.1

Type RM Length L Ch R = 1 ,80661.1 ,1098.6,1092.8,1085.4
XS GIS Cut Line= 4
     1539542.129      303591.561     1539703.587      304049.894
       1539773.9      304229.582      1539805.15      305086.352
#Sta/Elev= 30
       0   929.3    38.9  922.98    77.8  914.71   194.4  884.02   213.8  876.77
     243  861.85   252.7  857.72   262.4  854.59     311  843.54   340.2  835.54
   485.9  822.17   572.8  817.56   592.1  814.42   601.7  813.66   611.4  814.14
   640.3   817.4   727.6  818.02   786.1  819.52   795.8  820.56   815.3  824.39
     864  827.97   922.5  834.93   980.9  844.12  1049.1  861.58  1107.6  874.73
  1185.5  893.53  1214.7  899.49  1360.9  918.59  1399.8  919.82  1536.2  928.88
#Mann= 3 , 0 , 0
       0     .05       0   592.1    .045       0   611.4     .05       0
Bank Sta=592.1,611.4
XS Rating Curve= 0 ,0
Exp/Cntr=0.3,0.1

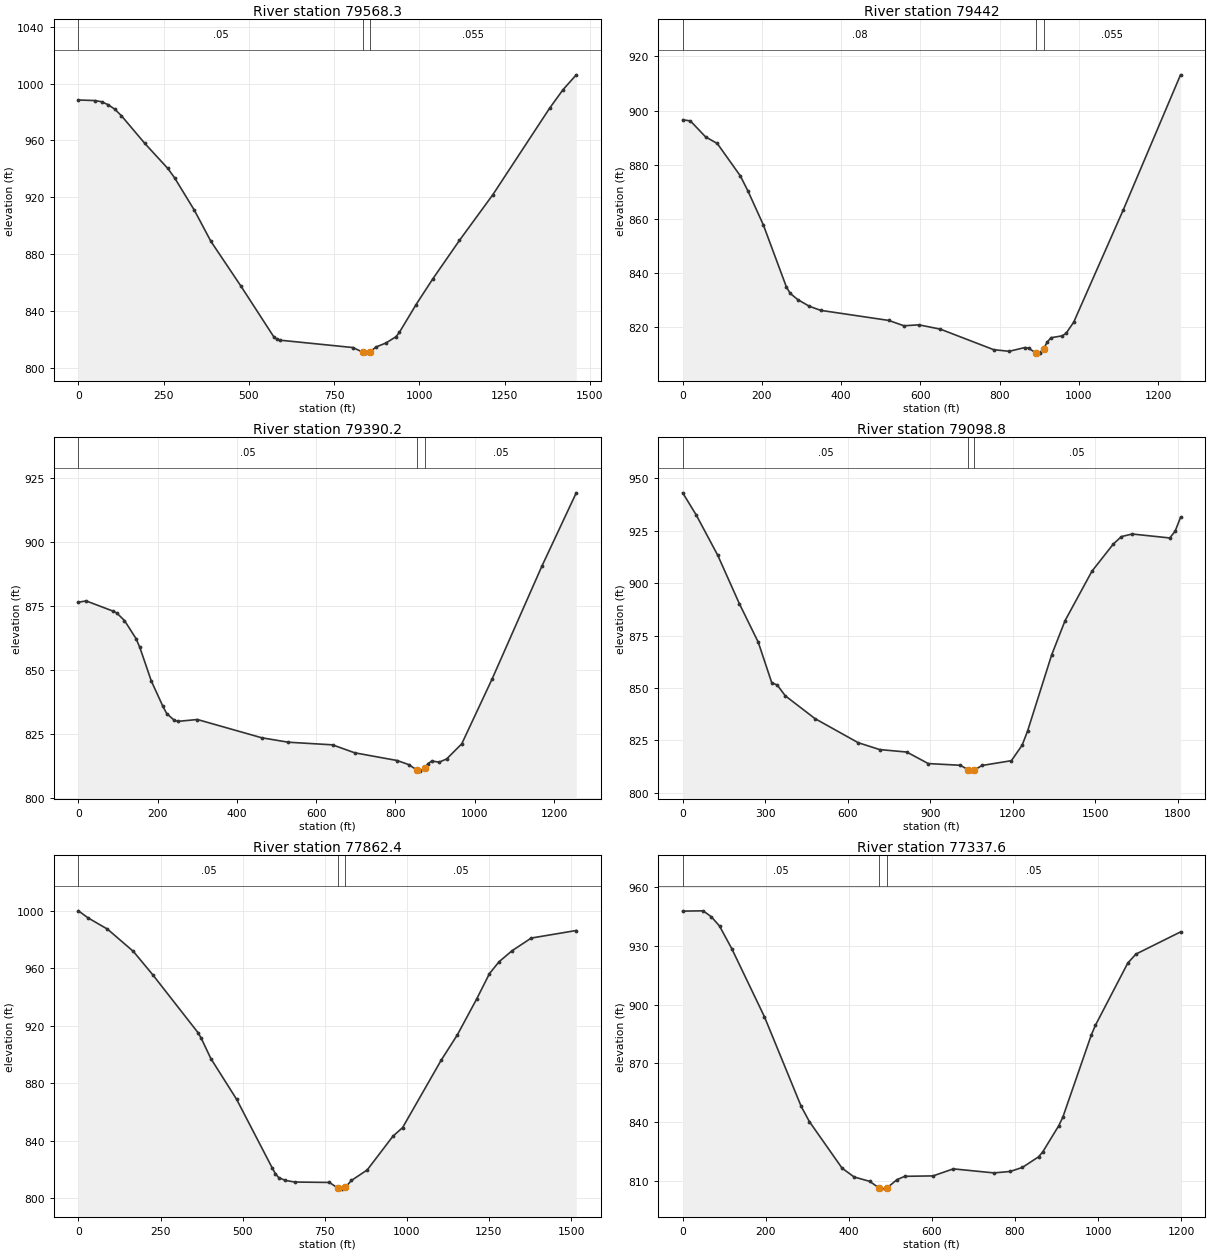
Type RM Length L Ch R = 1 ,79568.3 ,127.6,126.3,125.1
XS GIS Cut Line= 5
     1538716.608      304031.665     1538757.927        304574.2
     1538854.281      304764.304     1538942.823      304878.887
      1539328.24      305282.533
#Sta/Elev= 30
       0  988.48    48.6  988.08      68  987.24    87.4  985.13   106.9  981.96
   126.3  977.35   194.3  958.04   262.3  940.28   281.8  933.82   340.1  910.89
   388.6     889   476.1  857.72   573.2  821.79   582.9  820.04   592.5  819.47
   805.5   814.3   834.5  810.96   844.1  810.39   853.8  811.11   873.1  814.73
     902  817.54   931.4  821.94   941.2  824.95   990.2  844.51  1039.1  862.55
  1117.4  889.65  1215.4  921.84  1381.8  982.64    1421  995.66  1460.1 1006.18
#Mann= 3 , 0 , 0
       0     .05       0   834.5    .045       0   853.8    .055       0
Bank Sta=834.5,853.8
XS Rating Curve= 0 ,0
Exp/Cntr=0.3,0.1

Type RM Length L Ch R = 1 ,79442   ,52.7,51.8,51.6
XS GIS Cut Line= 6
     1538082.927      304435.311     1538324.247      304629.755
     1538667.997      304759.964     1538801.677      304902.325
     1538857.233      304966.561     1539062.094      305183.575
#Sta/Elev= 30
       0   896.6    19.4  896.18    58.1  890.24    87.2  887.87   145.3  875.93
   164.6  870.35   203.4  857.86   261.5     835   271.2  832.57   290.5  830.26
   319.5  827.82   348.1  826.31     520  822.59   558.2  820.62   595.9  820.97
   650.3  819.37   784.9  811.79     824  811.21     863  812.58   872.8  812.36
   891.7  810.53   901.1  810.62   910.5  812.17     920  814.66   929.4  816.21
   957.7  816.91   967.3  817.82   986.6  821.94  1111.8   863.4  1256.2  913.18
#Mann= 3 , 0 , 0
       0     .08       0   891.7    .045       0   910.5    .055       0
Bank Sta=891.7,910.5
XS Rating Curve= 0 ,0
Exp/Cntr=0.3,0.1

Type RM Length L Ch R = 1 ,79390.2 ,295.5,291.4,286.4
XS GIS Cut Line= 6
     1538067.302      304496.075     1538308.622      304690.519
     1538652.372      304820.727     1538786.052      304963.089
     1538841.608      305027.325     1539046.469      305244.339
#Sta/Elev= 30
       0  876.54    19.4  877.06    87.2  873.07    96.8  872.32   116.2  869.38
   145.3  862.32     155  858.82     184  845.66   213.1   835.8   222.8  832.96
   242.1  830.29   251.8  829.91   300.2  830.63   462.7  823.47   529.6  821.74
   641.2  820.71     697   817.6   804.4  814.57   833.7  812.96   853.3  810.92
     863  810.42     874  811.69   882.2  813.36   891.7  814.36   910.5  813.94
   929.4  815.22   967.3  821.12  1044.4  846.68  1169.5  890.67  1256.2  919.37
#Mann= 3 , 0 , 0
       0     .05       0   853.3    .045       0     874     .05       0
Bank Sta=853.3,874
XS Rating Curve= 0 ,0
Exp/Cntr=0.3,0.1

Type RM Length L Ch R = 1 ,79098.8 ,1227.9,1236.4,1243.9
XS GIS Cut Line= 4
     1537648.552      304701.804     1538393.344      305032.533
     1538661.573      305227.845      1539171.99      305652.325
#Sta/Elev= 30
       0   943.1    49.1  932.55   127.6  913.26   206.2  890.16   274.9  871.79
     324  852.42   343.6  851.41   373.1  846.24   481.1  835.36   638.2  823.86
   716.7  820.57   814.9   819.4     893   813.9  1010.1  813.08 1038.52810.9069
  1049.1  810.29  1058.9  810.64  1088.2  812.98  1195.5  815.28  1234.6   822.7
  1254.1  829.35    1342  865.79  1390.8  882.14  1488.4   905.7  1566.5  918.72
  1595.8  922.22  1634.9  923.45  1771.5  921.56  1791.1  924.82  1810.6  931.39
#Mann= 3 , 0 , 0
       0     .05       0 1038.52    .045       0  1058.9     .05       0
Bank Sta=1038.52,1058.9
XS Rating Curve= 0 ,0
Exp/Cntr=0.3,0.1

Type RM Length L Ch R = 1 ,77862.4 ,518.2,524.7,531.2
XS GIS Cut Line= 4
     1537513.136      305538.609     1537867.302      306094.165
      1537988.83      306278.193     1538419.386      306746.943
#Sta/Elev= 30
       0  999.97    29.5  995.04    88.5  987.23   167.2  971.76   226.2  955.52
   363.8  915.31   373.7  911.43   403.2  897.19   481.8  868.78     590  821.13
   599.8  817.06   609.7   814.4   629.3  812.44   658.8  811.27   764.3  810.98
  791.08 806.873   802.7  806.33   812.3  807.52   831.4  812.38   879.4  819.68
   957.7  843.16   987.1  849.14  1104.6  896.05  1153.6  913.59  1212.3  938.47
  1251.5  956.26  1280.8  964.53    1320  972.13  1378.8  981.02  1515.9  986.28
#Mann= 3 , 0 , 0
       0     .05       0  791.08    .045       0   812.3     .05       0
Bank Sta=791.08,812.3
XS Rating Curve= 0 ,0
Exp/Cntr=0.3,0.1

Type RM Length L Ch R = 1 ,77337.6 ,71.6,71.6,71.6
XS GIS Cut Line= 4
     1537311.747      305927.498     1537440.219      306309.877
     1537481.452      306444.425     1537652.893      307075.936
#Sta/Elev= 30
       0  947.76    49.2  947.91    68.9  944.88    88.6  940.16   118.1   928.6
   196.8   893.8   285.3  848.01     305  840.26   383.7  816.48   412.8  811.96
   450.3  809.74  473.07806.3077   478.4  805.77   491.5  806.34     516  810.64
   534.7  812.31   602.7  812.53   651.5  816.12   749.2  814.06   788.3  814.79
   817.6  816.84   856.6  822.25   866.4  824.66   905.5  838.22   915.2  842.55
   983.6  884.44   993.4  889.37  1071.5  921.23    1091   925.8  1198.5  937.14
#Mann= 3 , 0 , 0
       0     .05       0  473.07    .045       0   491.5     .05       0
Bank Sta=473.07,491.5
XS Rating Curve= 0 ,0
Exp/Cntr=0.3,0.1

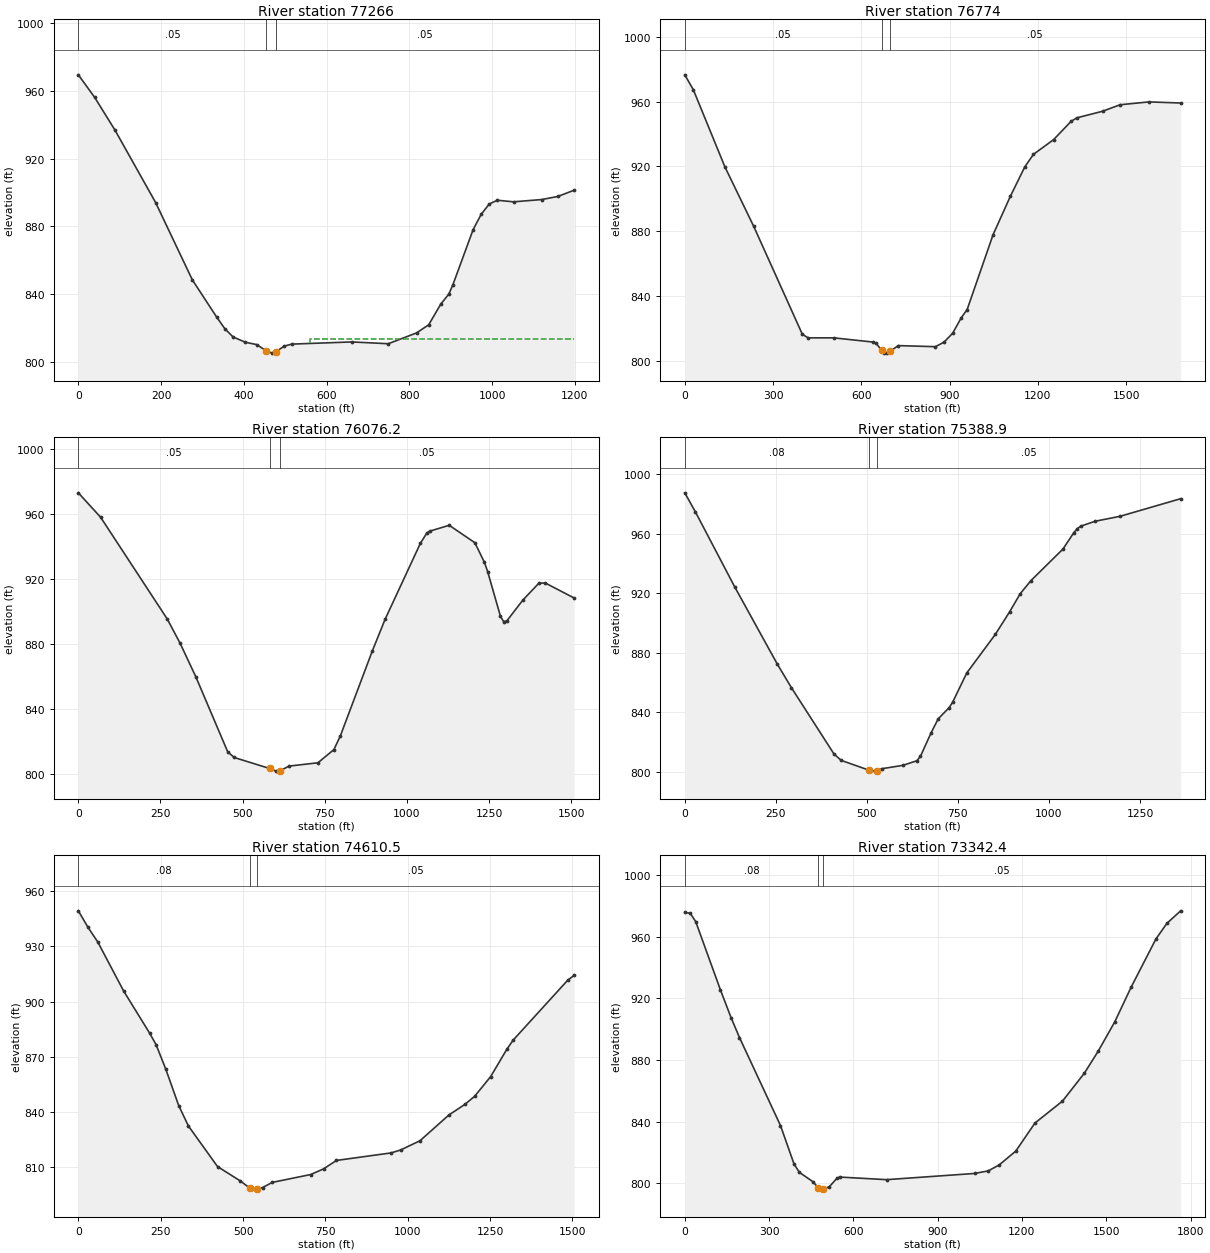
Type RM Length L Ch R = 1 ,77266   ,488.7,492,494.7
XS GIS Cut Line= 4
     1537245.775      305955.276     1537374.247      306337.654
     1537415.479      306472.203      1537586.92      307103.714
#Sta/Elev= 30
       0  969.53    39.4  956.25    88.6  936.89   186.9   894.1   275.5  848.53
   334.5  826.47   354.2  819.64   373.9  814.82   403.4  811.69   431.5  810.26
  454.38806.5502   469.1  805.24   476.8  805.82   497.2  809.34     516  810.56
   661.3  811.85   749.2  810.79   817.6  817.17   846.9  821.98   876.2  834.22
   895.7  840.16   905.5  845.68   954.3  878.17   973.8   887.2   993.4  893.31
  1012.9  895.49    1052  894.56  1120.3  895.91  1159.4  897.75  1198.5  901.44
#Mann= 3 , 0 , 0
       0     .05       0  454.38    .045       0   476.8     .05       0
#XS Ineff= 2 , 0
                          560.96          813.72
Permanent Ineff=
       F       F
Bank Sta=454.38,476.8
XS Rating Curve= 0 ,0
Exp/Cntr=0.3,0.1

Type RM Length L Ch R = 1 ,76774   ,684.8,697.8,710.7
XS GIS Cut Line= 4
      1536826.07      305929.379     1536923.487      306466.221
     1536965.154      306690.179     1537025.722      307600.386
#Sta/Elev= 30
       0  976.53    29.2  967.24   136.4  919.63   233.8  883.09   399.5  816.26
     419  814.01   506.6     814   640.5  811.39     650  810.78     669  806.28
   678.5  804.58     688  804.56   697.5  805.69     726   809.2   851.9  808.54
   881.3  811.34   910.7  816.89   940.2  826.52   959.8  831.46  1048.1  877.79
  1106.9  901.52    1156  919.71  1185.4  927.42    1254  936.52  1312.9  947.72
  1332.5  949.94  1420.8  954.05  1479.6  958.03  1577.7   959.8  1685.6  959.11
#Mann= 3 , 0 , 0
       0     .05       0     669    .045       0   697.5     .05       0
Bank Sta=669,697.5
XS Rating Curve= 0 ,0
Exp/Cntr=0.3,0.1

Type RM Length L Ch R = 1 ,76076.2 ,675.2,687.3,698.8
XS GIS Cut Line= 4
     1536381.625       306076.08     1536347.771      306529.205
     1536254.021      306745.351     1536118.604      307552.643
#Sta/Elev= 30
       0  972.99    67.7  957.99   270.7  895.24   309.4  880.48   357.7  859.62
   454.4  813.55     474  810.02     582  803.23   601.6  801.61   614.3  801.86
   640.9  804.71     729  806.75   777.7   814.9   797.2   823.3   894.6  875.68
   933.6  895.22  1040.8  941.94  1060.3  948.21    1070  949.44  1128.5     953
  1206.5  942.26  1235.7  930.14  1245.4  924.48  1284.4  896.94  1294.2   893.6
  1303.9  894.17  1352.6  906.96  1401.4  917.37  1420.9  917.45  1508.6   908.2
#Mann= 3 , 0 , 0
       0     .05       0     582    .045       0   614.3     .05       0
Bank Sta=582,614.3
XS Rating Curve= 0 ,0
Exp/Cntr=0.3,0.1

Type RM Length L Ch R = 1 ,75388.9 ,780.5,778.4,775.1
XS GIS Cut Line= 4
     1536255.757      305869.483     1535894.646      306119.483
     1535759.229      306220.178     1535148.118       306661.15
#Sta/Elev= 30
       0  987.35    29.3  974.48   136.6  924.39   253.8  872.41   292.8  856.46
   409.9  811.87   429.4  807.66   504.8  801.14   523.6  800.42  527.26800.7892
   542.3   802.1   598.6  804.28   637.3   807.4   647.1  810.35   676.5  826.23
     696   835.6   725.4  842.92   735.2  846.56   774.3  866.35   852.6  892.22
   891.8  907.33   921.1  919.58   950.5  928.38  1038.6  949.63    1068  960.47
  1077.7  963.29  1087.5  964.96  1126.7  968.25  1195.2  971.58  1361.6   983.4
#Mann= 3 , 0 , 0
       0     .08       0   504.8    .045       0  527.26     .05       0
Bank Sta=504.8,527.26
XS Rating Curve= 0 ,0
Exp/Cntr=0.3,0.1

Type RM Length L Ch R = 1 ,74610.5 ,1269,1268.2,1264.7
XS GIS Cut Line= 4
     1535912.441      305100.386     1535566.087      305420.698
     1535467.129      305514.448     1534691.955      305965.837
#Sta/Elev= 30
       0  949.39    29.5  940.37      59  932.45   137.6  905.74   216.2  882.92
   235.9  876.63   265.4  863.29   304.7  843.45   334.2  832.33   422.6  810.25
   491.2  802.51   520.4  798.57   539.9  797.99   542.7  798.04   559.4  798.86
   588.6  801.65   705.6  805.94   744.6  809.03   783.6   813.6   949.3  817.69
   978.6  819.31  1037.1  824.31  1124.8  838.32  1173.6  844.12  1202.8  848.46
  1251.6   859.2  1300.4  873.98  1319.8  879.03  1485.6  911.66  1505.1   914.3
#Mann= 3 , 0 , 0
       0     .08       0   520.4    .045       0   542.7     .05       0
Bank Sta=520.4,542.7
XS Rating Curve= 0 ,0
Exp/Cntr=0.3,0.1

Type RM Length L Ch R = 1 ,73342.4 ,781.9,786.7,790.4
XS GIS Cut Line= 4
     1535445.427       304063.06     1535139.872      304271.393
     1535004.455      304420.698       1534511.4      305507.504
#Sta/Elev= 30
       0  975.78    19.5  975.21    38.9   969.8   126.5  925.67   165.4  907.19
   194.6  894.62   340.6  837.51     389  812.47   408.2  807.08   456.2  801.09
   475.4  797.05     485  796.26   491.7   796.3   513.8   797.7   542.6  803.51
   552.2  804.08   718.1   802.4  1031.2  806.42  1080.1   808.1  1119.2  811.98
  1177.9   820.9  1246.4  839.16  1344.2  853.34  1422.4  871.53  1471.3  885.72
    1530  904.64  1588.7   927.3  1676.8  958.52  1715.9  968.68  1764.8  976.81
#Mann= 3 , 0 , 0
       0     .08       0   475.4    .045       0   491.7     .05       0
Bank Sta=475.4,491.7
XS Rating Curve= 0 ,0
Exp/Cntr=0.3,0.1