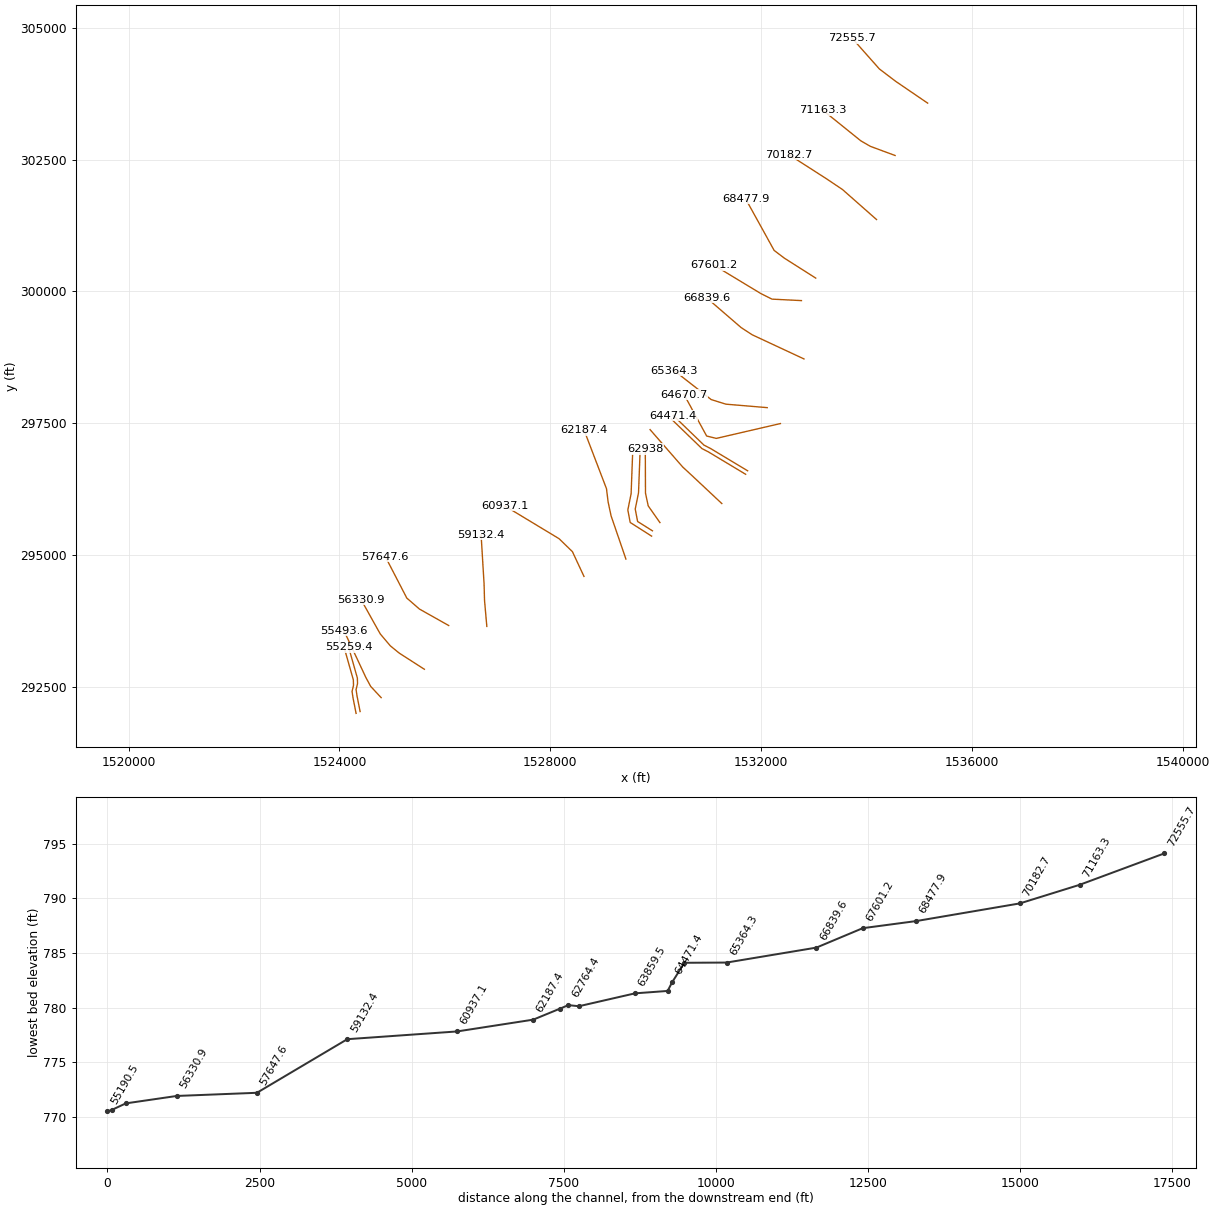
HEC-RAS study BNDSCR.prj: BNDSCR

--- BNDSCR.g01 (geometry) --- (continued)

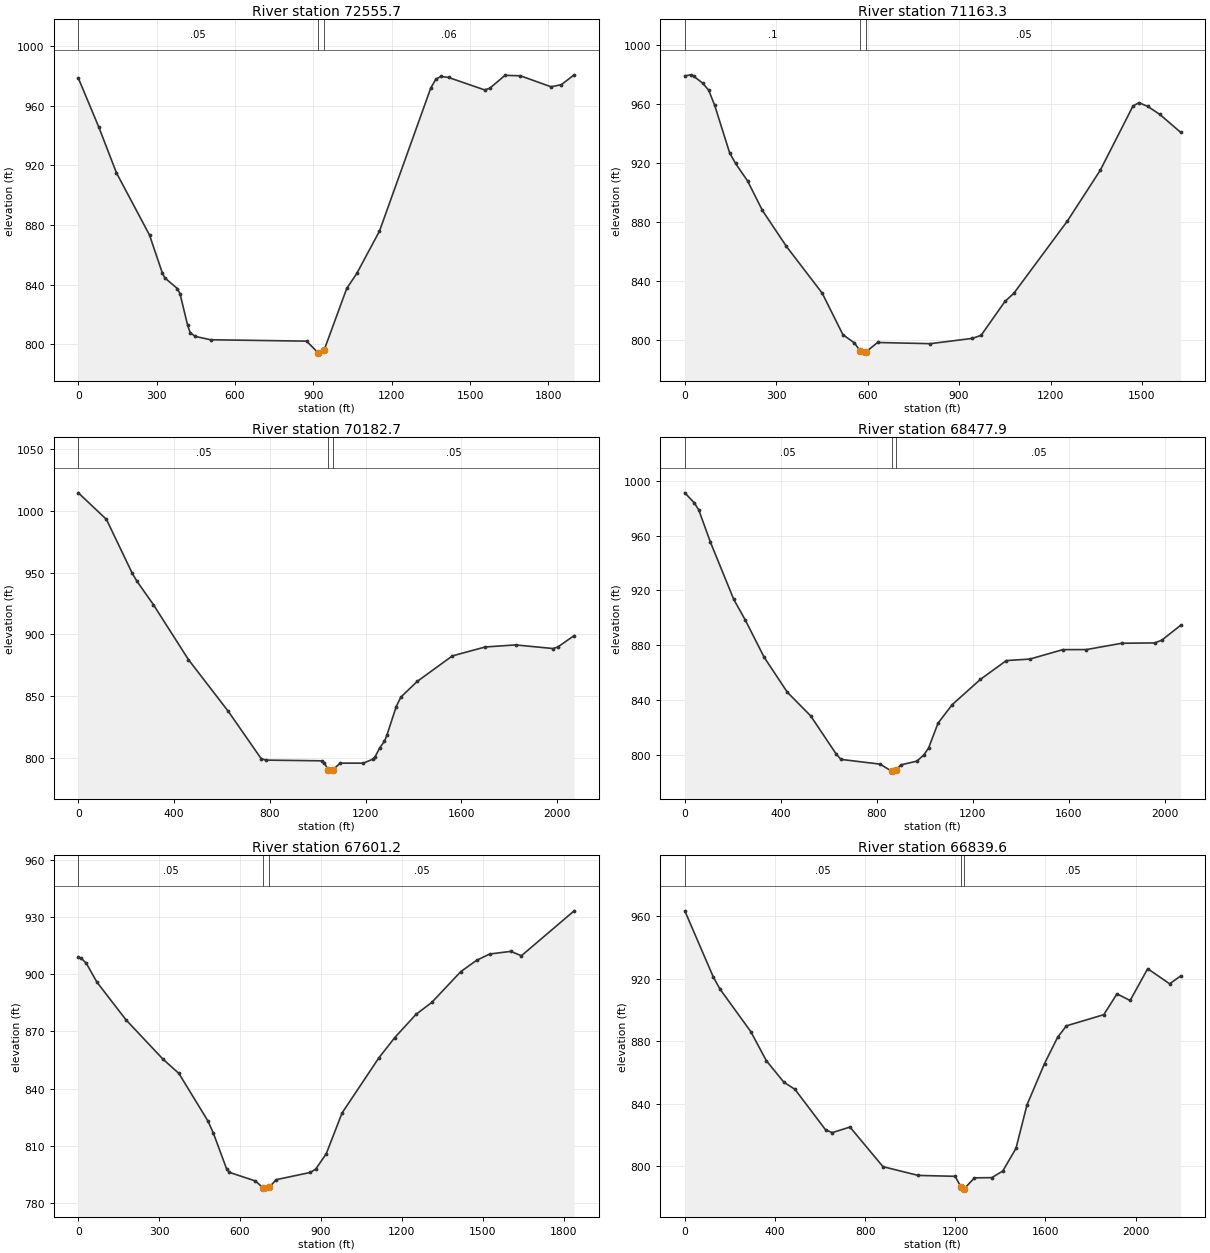
Type RM Length L Ch R = 1 ,72555.7 ,1388.9,1392.4,1395.3
XS GIS Cut Line= 4
     1535157.233      303570.004     1534546.122      303986.671
     1534240.566       304219.31     1533726.677      304799.171
#Sta/Elev= 30
       0  978.49    77.9  945.86     146  914.98   272.5  873.31   321.2  848.08
   330.9   844.6   379.6  837.37   389.3  833.92   418.5  812.84   428.2  807.86
   447.7  805.33   506.1  803.09     874  802.16  917.73794.3976   922.1  794.12
   941.3  796.26  1027.7  837.49  1066.1  847.52  1153.1  875.94  1349.2  971.75
  1368.9  977.78  1388.5  979.63  1417.9  978.92  1555.2  970.62  1574.8  971.63
  1633.7  980.35  1692.5  980.06  1810.2  972.68  1849.4   974.1  1898.5   980.7
#Mann= 3 , 0 , 0
       0     .05       0  917.73    .045       0   941.3     .06       0
Bank Sta=917.73,941.3
XS Rating Curve= 0 ,0
Exp/Cntr=0.3,0.1

Type RM Length L Ch R = 1 ,71163.3 ,981.1,980.6,978.2
XS GIS Cut Line= 4
     1534539.177      302576.948     1534070.427       302750.56
     1533889.872      302854.726     1533174.594      303431.115
#Sta/Elev= 30
       0  978.97    19.6  979.67    29.4  978.69    58.8  974.01    78.4  969.22
      98  959.08     147  926.92   166.6  919.64   205.8  907.89   254.8  887.81
   333.2  863.58   450.9  831.83   518.8  803.72   556.7  798.13   575.7  792.63
   585.1  791.24   594.6  792.09   632.5  798.44     806  797.65   942.9  801.21
   972.2  803.27  1050.4  826.22  1079.7  831.78  1255.6  880.77  1363.1  915.02
  1470.6  958.55  1490.1   960.8  1519.4  958.24  1558.5  952.88  1626.9  940.76
#Mann= 3 , 0 , 0
       0      .1       0   575.7    .045       0   594.6     .05       0
Bank Sta=575.7,594.6
XS Rating Curve= 0 ,0
Exp/Cntr=0.3,0.1

Type RM Length L Ch R = 1 ,70182.7 ,1705.8,1704.9,1703
XS GIS Cut Line= 4
     1534187.376      301362.054     1533541.543      301931.499
     1533235.358      302136.844     1532527.654      302591.221
#Sta/Elev= 30
       0 1014.44   117.4  992.97     225  949.48   244.6  943.07   313.1  924.19
   459.9  879.66   626.2  837.88   763.2  799.74   782.8  798.45  1016.3  797.88
    1026  796.45 1044.74790.3586  1055.1  789.54  1063.9  790.81  1093.9     796
  1190.9     796  1229.7  799.19  1239.5   801.2    1259  808.42  1278.6  813.78
  1288.4  818.43  1327.5  841.66    1347  849.39  1415.5  862.08  1562.2  882.68
  1699.1  889.86  1826.2  891.54  1982.7  888.61  2002.2  889.82  2070.7  899.06
#Mann= 3 , 0 , 0
       0     .05       0 1044.74    .045       0  1063.9     .05       0
Bank Sta=1044.74,1063.9
XS Rating Curve= 0 ,0
Exp/Cntr=0.3,0.1

Type RM Length L Ch R = 1 ,68477.9 ,872.1,876.7,880.1
XS GIS Cut Line= 4
     1533033.969      300251.428     1532443.691      300626.428
     1532245.775      300775.733     1531704.108        301754.9
#Sta/Elev= 30
       0  991.32    38.8  984.21    58.3  978.79   106.8  955.26     204  913.45
   252.5  898.22   330.2   871.3   427.4  845.56   524.5  828.32   631.3  800.32
   650.8   796.5   813.8  793.03   861.4  787.94     871  787.92  880.78 788.624
   899.6  792.45   966.9  795.22   996.3  799.78    1016  804.84  1055.2  822.97
  1114.1  836.47  1231.9  854.98  1339.9  868.72    1438  869.82  1575.4  876.72
  1673.6  876.76  1820.8  881.38  1958.3  881.63  1987.7  883.63  2066.2   894.5
#Mann= 3 , 0 , 0
       0     .05       0   861.4    .045       0  880.78     .05       0
Bank Sta=861.4,880.78
XS Rating Curve= 0 ,0
Exp/Cntr=0.3,0.1

Type RM Length L Ch R = 1 ,67601.2 ,764.2,761.5,758.7
XS GIS Cut Line= 4
     1532763.136      299824.344     1532204.108      299852.122
     1531995.775      299956.289     1531099.941      300497.955
#Sta/Elev= 30
       0  908.88     9.8  908.53    29.5  905.79    68.7  895.94   176.8   876.1
   314.2  855.44   373.1  847.97   481.2  822.93   500.8  816.71   549.9  797.98
   559.7   796.1   656.8  791.56   685.9  787.86   695.6  787.27  708.08788.2728
   734.4  792.24   861.1  796.04   880.7  797.78   919.8  805.85   978.5  827.24
  1115.5  856.26  1174.2  866.82  1252.5  878.93  1311.2  885.23  1418.8  901.38
  1477.5  907.31  1526.4  910.64  1604.7  912.02  1643.8  909.72  1839.5  933.29
#Mann= 3 , 0 , 0
       0     .05       0   685.9    .045       0  708.08     .05       0
Bank Sta=685.9,708.08
XS Rating Curve= 0 ,0
Exp/Cntr=0.3,0.1

Type RM Length L Ch R = 1 ,66839.6 ,1468.7,1475.3,1481.3
XS GIS Cut Line= 4
     1532811.747      298717.573     1531829.108      299175.907
     1531620.775      299311.323     1530964.525      299877.296
#Sta/Elev= 30
       0  963.28     127  920.83   156.3  913.25     293  886.07   361.4   867.6
   439.6  853.78   488.4  849.28   625.2  823.25   654.5  821.58   732.6  825.16
   879.1  799.84  1035.4  794.25    1199  793.68  1224.2  787.13  1237.2  785.49
  1239.2  785.73    1285   792.7    1362  792.83  1410.6  797.09  1469.1  811.55
  1517.8  839.28  1595.6   865.7  1654.1  882.57    1693  889.82  1858.6  896.94
    1917  910.24  1975.4     906  2053.3  926.31  2150.7  916.67  2199.4  921.66
#Mann= 3 , 0 , 0
       0     .05       0  1224.2    .045       0  1239.2     .05       0
Bank Sta=1224.2,1239.2
XS Rating Curve= 0 ,0
Exp/Cntr=0.3,0.1

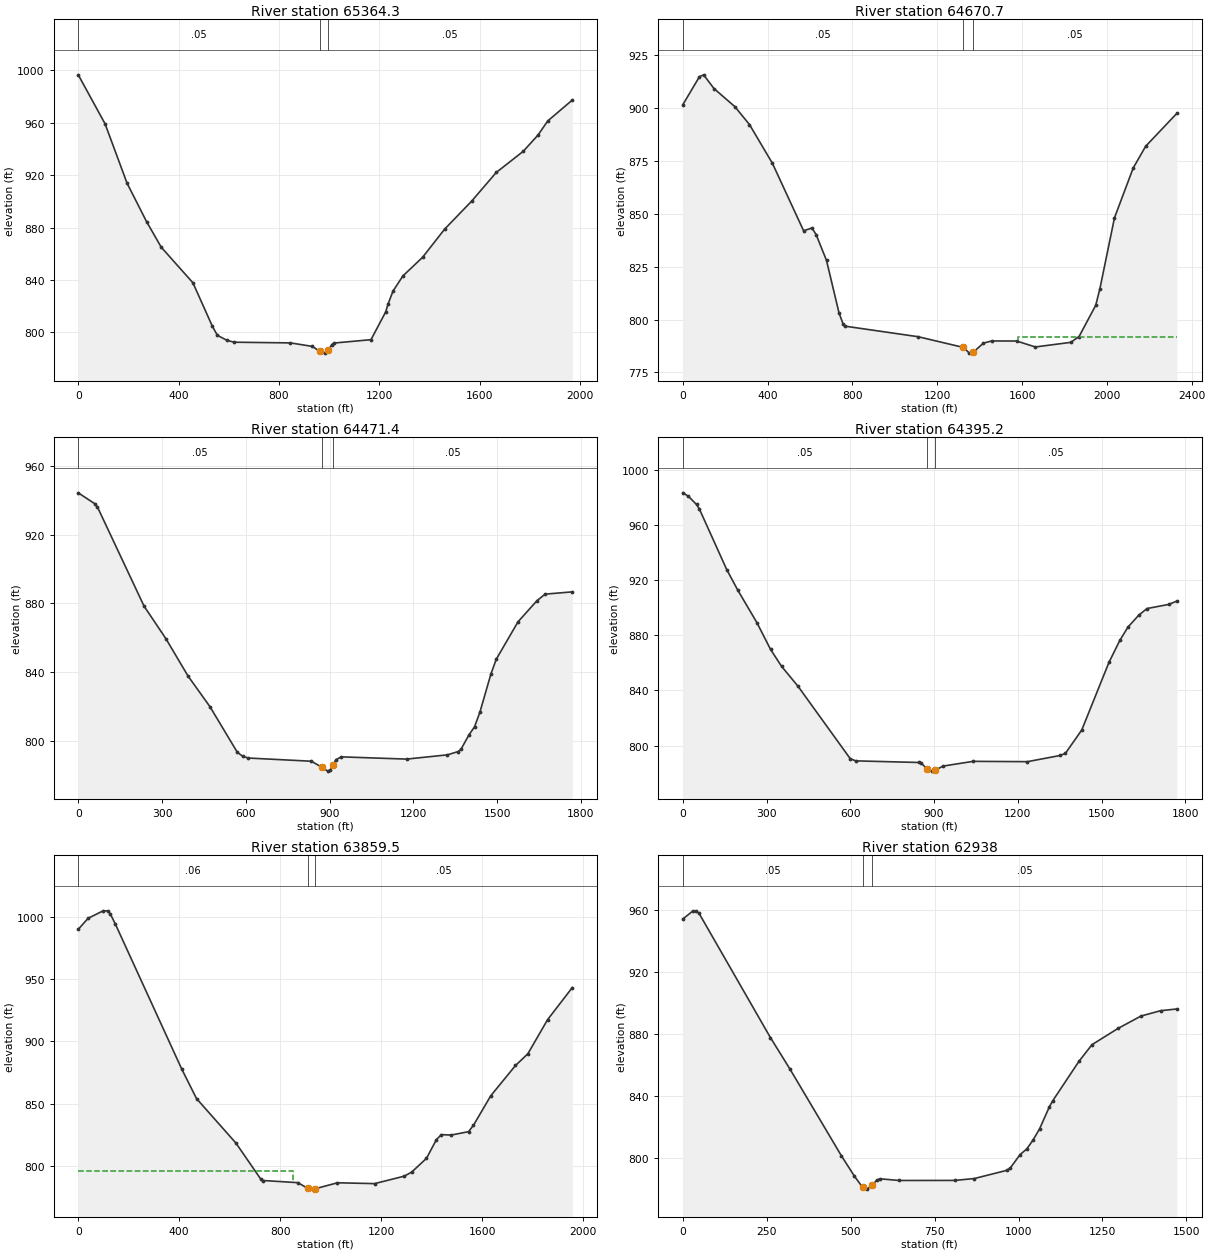
Type RM Length L Ch R = 1 ,65364.3 ,691.9,693.6,694.7
XS GIS Cut Line= 4
      1532113.83      297793.962     1531329.108      297859.935
      1531051.33       297946.74     1530349.941      298495.351
#Sta/Elev= 30
       0  996.69   106.9  959.27   194.4  913.97   272.2  884.58   330.6  865.05
   456.9  837.86   534.7  804.56   554.2  797.78     593  793.83   622.2  792.46
   845.7  791.93     933  789.26   962.1  785.52   981.5  784.12  995.96786.3232
  1010.6  790.68  1020.3  791.84  1166.6  794.39  1225.3  815.64  1235.1   821.9
  1254.6  831.59  1293.8  843.08  1372.1   857.3  1460.1  878.82  1567.8  900.22
  1665.6  922.09  1773.3  938.26    1832  950.62  1871.1  961.48    1969  977.45
#Mann= 3 , 0 , 0
       0     .05       0   962.1    .045       0  995.96     .05       0
Bank Sta=962.1,995.96
XS Rating Curve= 0 ,0
Exp/Cntr=0.3,0.1

Type RM Length L Ch R = 1 ,64670.7 ,204.5,199.4,193.8
XS GIS Cut Line= 4
      1532363.83      297491.879     1531148.552      297210.629
     1530964.525      297255.768     1530537.441       298040.49
#Sta/Elev= 30
       0   901.7    78.6  914.98    98.2  915.85   147.3  909.32   245.6  900.78
   314.3  892.33   422.4     874   569.7  842.03     609  843.34   628.6  840.25
   677.7  827.99   736.6  803.19   756.3  797.78   766.1  796.85  1109.9  791.87
  1323.2   786.8  1351.6   784.1  1370.6   784.6  1417.9  788.84  1456.5  789.86
  1574.3  789.83  1662.7  787.02  1829.6   789.2  1868.9  791.97  1947.4  806.73
    1967  814.53  2035.8  848.13  2124.1  871.72    2183  882.04  2330.3  897.64
#Mann= 3 , 0 , 0
       0     .05       0  1323.2    .045       0  1370.6     .05       0
#XS Ineff= 2 , 0
                         1581.06          791.51
Permanent Ineff=
       F       F
Bank Sta=1323.2,1370.6
XS Rating Curve= 0 ,0
Exp/Cntr=0.3,0.1

Type RM Length L Ch R = 1 ,64471.4 ,76.2,76.2,76.2
XS GIS Cut Line= 4
     1531742.302      296596.046     1531043.662      297016.242
     1530913.454      297083.517      1530332.58      297644.657
#Sta/Elev= 30
       0  944.28    58.9  937.97    68.8  936.02   235.7  878.34   314.3  859.31
   392.9  837.74   471.5  819.88   569.7   793.3   589.4  790.91     609  789.95
   834.8  788.09   873.9   784.5   893.4  782.33   903.2  782.97     913  785.92
   922.8  788.96   942.3  790.63  1175.9  789.33  1321.9   791.8  1360.8  793.73
  1370.5  794.99  1399.7  803.55  1419.2  808.09  1438.6  816.72  1477.6  838.69
    1497  847.44  1574.9  869.22    1643  881.55  1672.2  885.33  1769.5  886.65
#Mann= 3 , 0 , 0
       0     .05       0   873.9    .045       0     913     .05       0
Bank Sta=873.9,913
XS Rating Curve= 0 ,0
Exp/Cntr=0.3,0.1

Type RM Length L Ch R = 1 ,64395.2 ,541.7,535.7,529.5
XS GIS Cut Line= 4
     1531704.108      296530.073     1531005.468       296950.27
     1530875.259      297017.545     1530294.386      297578.685
#Sta/Elev= 30
       0  983.24    19.6  980.84    49.1  974.78    58.9  971.73   157.2  927.64
   196.4  912.87   265.2   889.2   314.3  869.73   353.6   857.5   412.6  843.03
   599.2  790.66   618.8  788.96   844.6  787.79   854.4  787.19   873.9   783.4
   893.4  781.52   903.2   782.2   932.5  785.19  1039.7  788.61  1234.3  788.38
  1351.1  792.86  1370.5  794.47  1428.9  811.38  1526.2  860.37  1565.1  876.27
  1594.3  885.95  1633.2  894.61  1662.4  899.37  1740.3  902.36  1769.5   904.8
#Mann= 3 , 0 , 0
       0     .05       0   873.9    .045       0   903.2     .05       0
Bank Sta=873.9,903.2
XS Rating Curve= 0 ,0
Exp/Cntr=0.3,0.1

Type RM Length L Ch R = 1 ,63859.5 ,935.1,921.5,907.3
XS GIS Cut Line= 4
     1531252.719      295974.518     1530697.163      296495.351
     1530509.663      296668.962     1529891.608      297377.296
#Sta/Elev= 30
       0  989.94      39  998.78    97.6 1004.69   117.2 1004.79   126.9 1002.38
   146.4  994.44     410  877.68   468.6  853.98   624.8  818.24   722.5  789.48
   732.2  788.22   869.6  786.49   908.9  781.98   928.6   781.3   938.4  781.59
  1026.8   786.4  1173.7  785.72  1291.2  791.71  1320.6  794.96  1379.4  806.04
  1418.5  820.98  1438.1  825.04  1477.3  824.73  1545.8  827.43  1565.4  832.56
    1634  856.28  1731.9  880.58  1780.9  889.99  1859.2  917.45  1957.1   943.2
#Mann= 3 , 0 , 0
       0     .06       0   908.9    .045       0   938.4     .05       0
#XS Ineff= 2 , 0
          849.93  795.95
Permanent Ineff=
       F       F
Bank Sta=908.9,938.4
XS Rating Curve= 0 ,0
Exp/Cntr=0.3,0.1

Type RM Length L Ch R = 1 ,62938   ,182.9,173.6,164.8
XS GIS Cut Line= 4
     1530079.108      295613.407     1529856.886      295929.379
     1529804.802      296172.435      1529801.33       297009.24
#Sta/Elev= 30
       0  954.02      29  958.99    38.6  959.28    48.3   957.7   260.8  877.73
   318.7  857.58   472.3   801.6   510.6  788.65  535.57781.2245   548.8  780.12
  563.27782.5995   577.5  785.78   587.1  786.77   644.6  785.69     810  785.73
   868.4  786.94   965.7  792.25   975.4  793.74  1004.6  802.35  1024.1   805.9
  1043.5  811.78    1063  819.07  1092.2  833.28  1101.9  837.03  1179.8  862.34
  1218.7  873.11  1296.5   883.6  1364.6  891.53    1423  894.98  1471.7   896.1
#Mann= 3 , 0 , 0
       0     .05       0  535.57    .045       0  563.27     .05       0
Bank Sta=535.57,563.27
XS Rating Curve= 0 ,0
Exp/Cntr=0.3,0.1

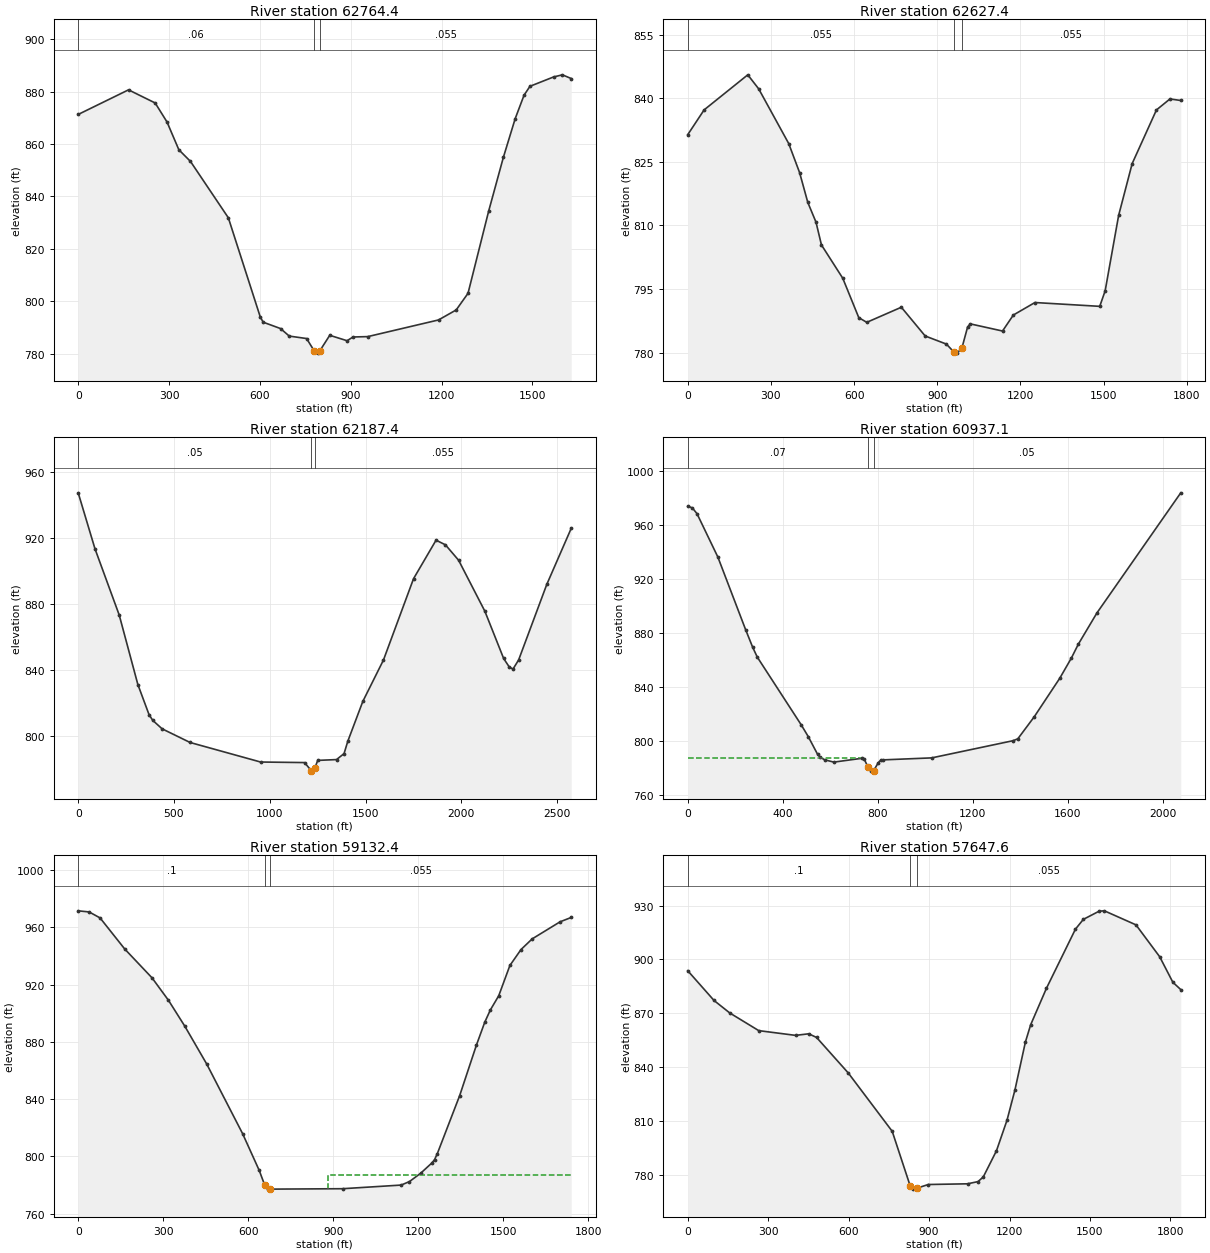
Type RM Length L Ch R = 1 ,62764.4 ,137.8,137,136.2
XS GIS Cut Line= 5
     1529936.747      295457.157     1529655.497       295634.24
     1529610.358      295870.351     1529672.858      296179.379
     1529700.636      296918.962
#Sta/Elev= 30
       0  871.29   166.2  880.68   254.2  875.67   293.2  868.44   332.4  857.82
   370.8  853.37   495.8  831.87   601.4  793.98     611  792.02   668.3  789.59
     697  786.72   754.3  785.79   780.1  780.94   792.5  780.22  797.76781.0679
   830.7  787.02     888  784.95   907.5  786.38   956.2  786.52  1189.9  792.88
  1248.3   796.7  1287.3  803.04  1355.5  834.41  1404.2  854.98  1443.1  869.69
  1472.3  878.62  1491.8  882.03  1569.7  885.59  1598.9  886.41  1628.1     885
#Mann= 3 , 0 , 0
       0     .06       0   780.1    .045       0  797.76    .055       0
Bank Sta=780.1,797.76
XS Rating Curve= 0 ,0
Exp/Cntr=0.3,0.1

Type RM Length L Ch R = 1 ,62627.4 ,431.4,440.1,447.2
XS GIS Cut Line= 5
     1529921.266       295356.52     1529514.872      295616.011
     1529469.733      295852.122     1529532.233       296161.15
     1529560.011      296900.733
#Sta/Elev= 30
       0  831.41      59  837.25   216.5  845.52   255.8  842.22   364.1  829.32
   403.4  822.46     433  815.43   462.5  810.79   482.2  805.41   559.1  797.55
   616.8  788.27   645.6  787.16   770.3  790.72   856.3  783.94   932.8  782.03
   961.4  780.05     971   779.9   988.6  781.07  1009.2  786.04  1018.7   786.8
  1135.2  785.11  1174.2  788.88  1252.1  791.83  1485.8  790.93  1505.3  794.58
    1554  812.39  1602.7  824.58  1690.3  837.24    1739  839.83    1778  839.47
#Mann= 3 , 0 , 0
       0    .055       0   961.4    .045       0   988.6    .055       0
#XS Ineff= 2 , 0
          769.23  790.48
Permanent Ineff=
       F       F
Bank Sta=961.4,988.6
XS Rating Curve= 0 ,0
Exp/Cntr=0.3,0.1

Type RM Length L Ch R = 1 ,62187.4 ,1234.5,1250.3,1265.2
XS GIS Cut Line= 5
     1529433.275      294922.435     1529152.025      295741.879
     1529096.469      296002.296     1529065.219      296255.768
     1528641.608      297363.407
#Sta/Elev= 30
       0  947.44    87.6  913.56   214.2  873.42   311.5  831.34   369.9   813.1
   389.4  809.61     438  804.52   584.1  796.24     952  784.41  1181.8  784.07
  1216.4  779.25    1221  778.89 1235.37780.7305  1250.5  785.39  1348.7  785.88
    1388  789.51  1407.6  797.02    1486  821.12  1593.8  846.21  1750.7  895.43
  1868.3  918.76  1917.3  915.95  1985.9  906.63  2123.1  875.74  2221.1  847.13
  2250.5  841.95  2270.1  840.72  2299.5  846.26  2446.5  892.01  2573.9  925.92
#Mann= 3 , 0 , 0
       0     .05       0  1216.4    .045       0 1235.37    .055       0
Bank Sta=1216.4,1235.37
XS Rating Curve= 0 ,0
Exp/Cntr=0.3,0.1

Type RM Length L Ch R = 1 ,60937.1 ,1821.4,1804.7,1786.7
XS GIS Cut Line= 4
     1528638.136      294592.573     1528419.386      295061.323
     1528165.913      295307.851     1527133.795      295931.115
#Sta/Elev= 30
       0  974.18    19.5  972.88      39   968.6   126.9  936.45     244  882.55
   273.3   869.7   292.8  862.34   478.2  812.04   507.5  803.43   546.8   790.3
   556.6  788.28   576.2  786.23   615.5  784.49   733.4  787.31   743.2  786.79
   759.8  780.55   772.6  777.81   782.5  778.01   802.1  783.92   811.9  785.75
   821.8  786.14  1027.7  787.63  1370.8  800.38  1390.4  801.79    1459  817.97
  1566.8   846.6  1615.9  861.63  1645.3  871.94  1723.7   895.1  2076.6  984.06
#Mann= 3 , 0 , 0
       0     .07       0   759.8    .045       0   782.5     .05       0
#XS Ineff= 2 , 0
          731.45  787.28
Permanent Ineff=
       F       F
Bank Sta=759.8,782.5
XS Rating Curve= 0 ,0
Exp/Cntr=0.3,0.1

Type RM Length L Ch R = 1 ,59132.4 ,1463.9,1484.8,1503.6
XS GIS Cut Line= 4
     1526795.254      293643.789     1526751.851       294134.24
      1526743.17       294446.74     1526686.747        295379.9
#Sta/Elev= 30
       0  971.48    38.6   970.7    77.2  966.53   164.1  944.84   260.7  924.64
   318.6  908.98   376.5  890.82   453.8  864.39   580.3   815.8   638.9  790.14
   658.4  779.78   668.2  777.15     678   777.1   932.9  777.39  1139.6  779.93
  1169.1  782.39  1208.5  788.19  1247.8  795.32  1257.7  797.74  1267.5  801.98
  1346.2  842.43  1405.3  877.69  1434.8  893.73  1454.5  902.26    1484  912.15
  1523.4  933.31  1562.7  944.46  1602.1  951.89  1700.5  963.81  1739.8  966.85
#Mann= 3 , 0 , 0
       0      .1       0   658.4    .045       0     678    .055       0
#XS Ineff= 2 , 0
                          881.94          786.88
Permanent Ineff=
       F       F
Bank Sta=658.4,678
XS Rating Curve= 0 ,0
Exp/Cntr=0.3,0.1

Type RM Length L Ch R = 1 ,57647.6 ,1316.5,1316.7,1315.7
XS GIS Cut Line= 4
     1526072.163       293661.15     1525516.608       293973.65
     1525277.025      294181.983     1524870.775      294966.705
#Sta/Elev= 30
       0  893.71    98.1  877.15   156.9  870.19   264.8  860.38   402.1  857.74
   451.1  858.62   480.5  856.58   598.2   836.9   762.5  804.37   829.8  773.86
   839.5  772.19  854.82772.7374   897.2  774.76  1043.3  775.15  1082.6  776.38
  1102.2  778.99  1151.3  793.53  1190.6  810.52    1220  827.24  1259.3   854.1
  1278.9  863.66  1337.8  883.98  1445.8  916.84  1475.3  922.29  1534.2  926.84
  1553.8  927.04  1671.6  919.23    1760  901.49  1809.1  887.29  1838.6  883.22
#Mann= 3 , 0 , 0
       0      .1       0   829.8    .045       0  854.82    .055       0
Bank Sta=829.8,854.82
XS Rating Curve= 0 ,0
Exp/Cntr=0.3,0.1

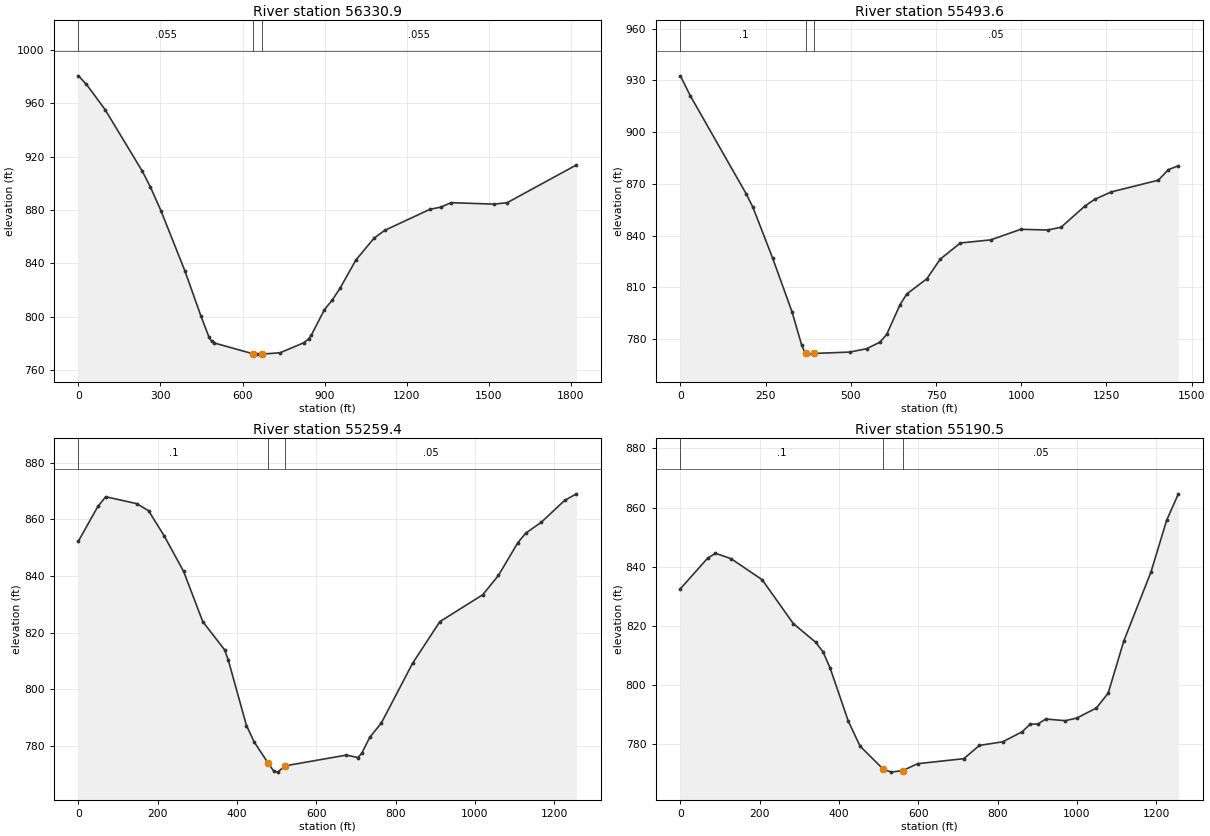
Type RM Length L Ch R = 1 ,56330.9 ,845.1,837.3,829
XS GIS Cut Line= 5
     1525610.358      292831.289     1525134.663      293136.844
     1524964.525      293275.733     1524773.552      293501.428
     1524412.441      294147.261
#Sta/Elev= 30
       0  980.75    29.2  974.37    97.5  955.41     234  909.01   263.2  897.28
   302.2  879.27   389.9  833.97   448.4  800.18   477.6  784.49   487.4   781.5
   497.1  780.23  637.07772.2219   651.3   771.9   670.4  771.91   737.3  772.92
   823.2  780.38   842.2  783.47   851.8  786.31   899.4  805.32   928.1  812.53
   956.7  821.42  1013.9  842.42  1080.6   858.9  1119.6  864.76  1285.1  880.59
    1324   882.2    1363  885.56  1518.8  884.46  1567.4  885.54  1820.6  913.88
#Mann= 3 , 0 , 0
       0    .055       0  637.07    .045       0   670.4    .055       0
Bank Sta=637.07,670.4
XS Rating Curve= 0 ,0
Exp/Cntr=0.3,0.1

Type RM Length L Ch R = 1 ,55493.6 ,250.8,234.2,217.4
XS GIS Cut Line= 4
     1524790.913      292293.094     1524592.997        292504.9
     1524499.247      292678.511     1524086.052      293560.455
#Sta/Elev= 30
       0  932.59      29  921.06   193.3  864.08   212.6  856.45   270.6  826.91
   327.5  795.77   355.6   776.6     365  772.24  369.52771.7495   374.4  771.22
     392  771.62     497  772.41   546.2  774.36   585.6  778.16   605.2  782.66
   644.6  799.97   664.3  806.09   723.3  814.97   762.6  826.35   821.7  835.69
   910.2  837.45   998.8  843.61  1077.5  843.18  1116.8  844.79  1185.7  856.88
  1215.2  860.94  1264.4  865.29  1402.1  872.06  1431.6  878.16  1461.1  880.47
#Mann= 3 , 0 , 0
       0      .1       0  369.52    .045       0     392     .05       0
Bank Sta=369.52,392
XS Rating Curve= 0 ,0
Exp/Cntr=0.3,0.1

Type RM Length L Ch R = 1 ,55259.4 ,69.4,68.8,68.9
XS GIS Cut Line= 6
     1524391.608      292029.205      1524332.58      292327.817
     1524315.219      292445.872     1524342.997      292560.455
     1524339.525      292664.622     1524172.858      293251.428
#Sta/Elev= 30
       0  852.34    49.1  864.62    68.7  868.03   147.3  865.58   176.7  863.08
     216  854.26   265.1  841.66   313.6  823.85   368.6  813.88   377.8  810.32
   423.7   787.1   443.4  781.26   478.5  773.77   492.5  771.01   502.3  770.61
     522  772.86   675.4  776.63   704.9  775.78   714.7   777.3   734.4  782.87
   763.9  787.99   842.6   809.1   911.5  823.85  1019.7  833.37  1059.1  840.17
  1108.3   851.8    1128  855.14  1167.3  859.01  1226.3  866.75  1255.9  869.06
#Mann= 3 , 0 , 0
       0      .1       0   478.5    .045       0     522     .05       0
Bank Sta=478.5,522
XS Rating Curve= 0 ,0
Exp/Cntr=0.3,0.1

Type RM Length L Ch R = 1 ,55190.5 ,706.3,743.2,778.1
XS GIS Cut Line= 6
     1524315.219      291994.483     1524256.191      292293.094
      1524238.83       292411.15     1524266.608      292525.733
     1524263.136        292629.9     1524096.469      293216.705
#Sta/Elev= 30
       0  832.56    68.7  842.89    88.4  844.54   127.6  842.73   206.2   835.6
   284.8  820.75   341.1  814.45   359.5  811.26   377.8  805.65   423.7  787.65
   453.2  779.28   511.2  771.54   531.8   770.5   560.6  771.03   598.5  773.36
   714.7  775.05   754.1  779.54   813.1  780.77   862.3  784.18     882  786.74
   901.6  786.77   921.3  788.48   970.5   787.9    1000  788.81  1049.2  792.21
  1078.8  797.21  1118.1   814.8    1187   838.3  1226.3  855.71  1255.9  864.66
#Mann= 3 , 0 , 0
       0      .1       0   511.2    .045       0   560.6     .05       0
Bank Sta=511.2,560.6
XS Rating Curve= 0 ,0
Exp/Cntr=0.3,0.1