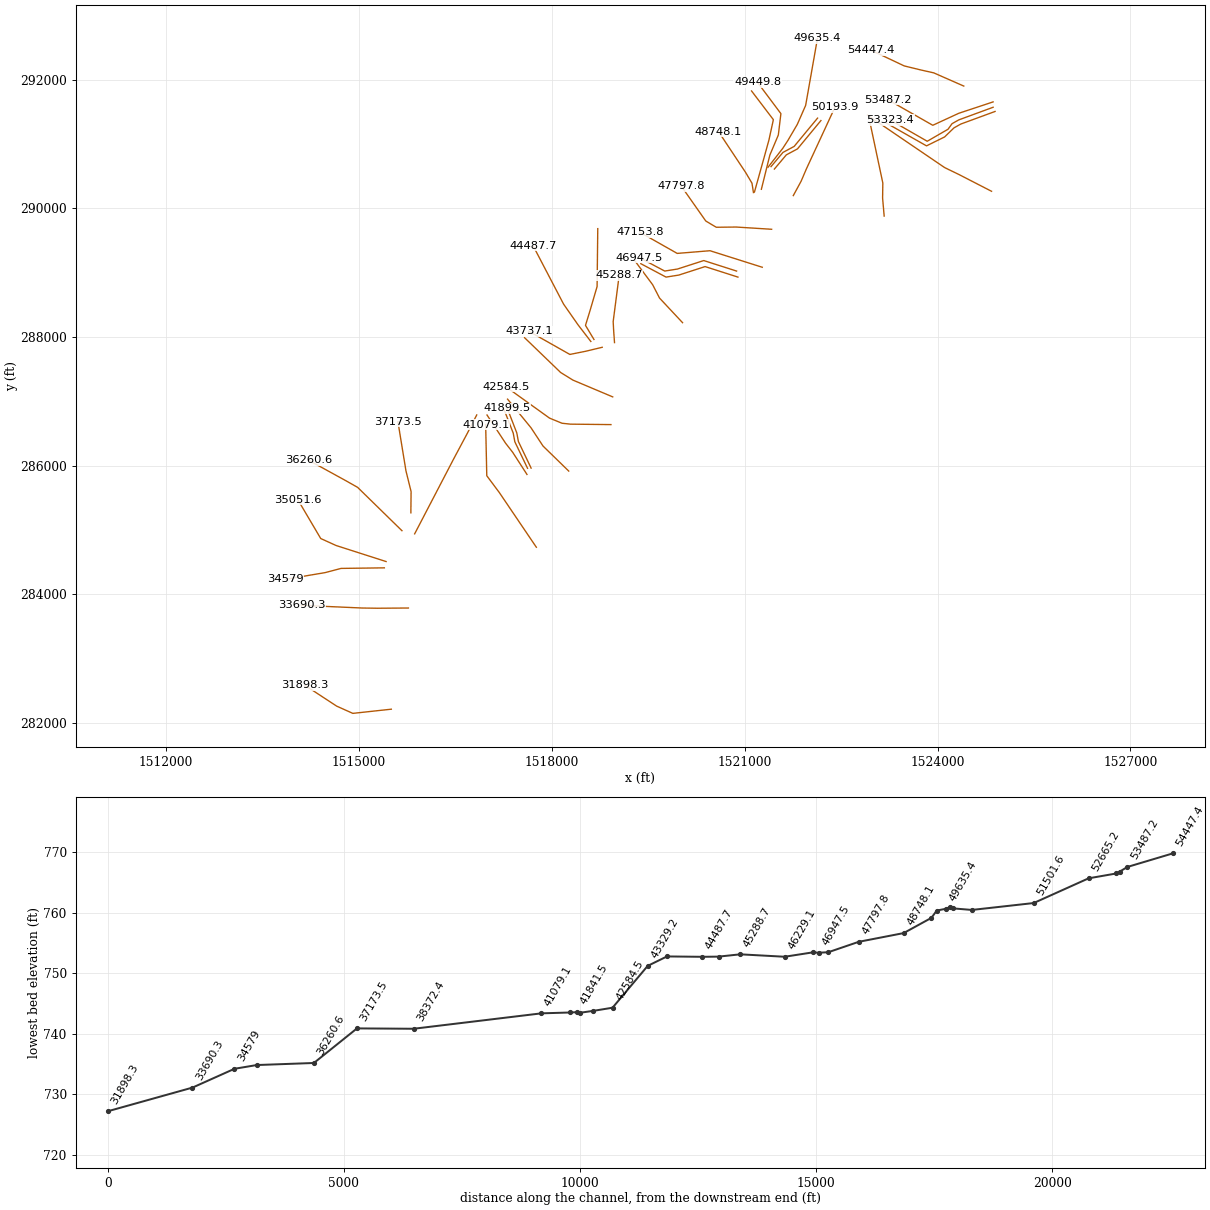
HEC-RAS study BNDSCR.prj: BNDSCR

--- BNDSCR.g01 (geometry) --- (continued)

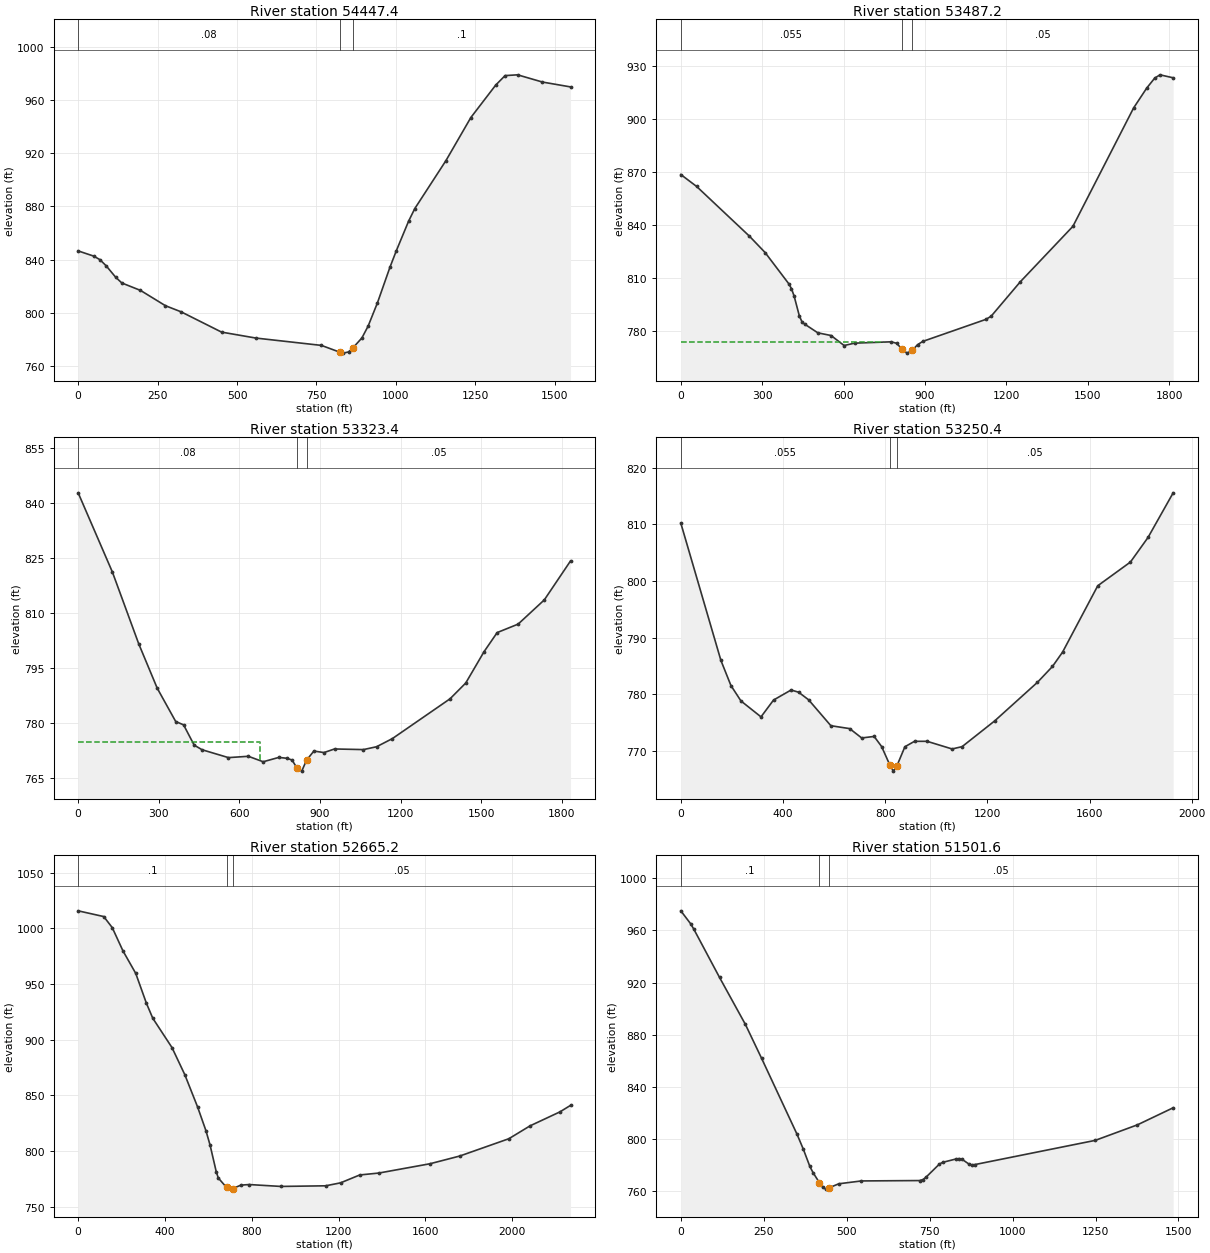
Type RM Length L Ch R = 1 ,54447.4 ,944.4,960.2,975.6
XS GIS Cut Line= 5
     1524407.378      291900.357     1523940.219      292105.594
      1523738.83      292150.733     1523481.886      292213.233
     1522967.997      292456.289
#Sta/Elev= 30
       0  846.62    49.1  842.69    68.7     840    88.3  835.37   117.8   826.9
   137.4  822.51   196.2  816.93   274.8  805.42   323.8  800.86   451.4  785.59
   559.4  781.12   765.6  775.61   824.4  770.42   834.2   769.8     851   770.7
   863.6  773.46   892.9  781.17   912.5  790.04   941.9  807.57   981.1  834.21
  1000.7  846.34  1039.9  868.91  1059.5  878.43  1157.5  914.45  1235.9  946.83
  1314.3  971.25  1343.7  978.34  1382.9  978.92  1461.3  973.49  1549.6  969.84
#Mann= 3 , 0 , 0
       0     .08       0   824.4    .045       0   863.6      .1       0
Bank Sta=824.4,863.6
XS Rating Curve= 0 ,0
Exp/Cntr=0.3,0.1

Type RM Length L Ch R = 1 ,53487.2 ,160.6,163.8,166.7
XS GIS Cut Line= 4
      1524863.83      291654.205     1524329.108      291477.122
     1523925.607      291290.982     1523224.218      291690.288
#Sta/Elev= 30
       0  868.77    58.3  862.02   252.5   833.9   310.8  824.55   398.2  806.82
   407.9  804.07   417.6  799.92     437  788.58   446.7  785.27   456.4     784
     505  779.06   553.6  777.55   601.9  771.88   640.6  773.22   775.8  773.97
   795.1  773.14   814.4  770.01   833.8  767.56   853.1  769.14   872.4  772.32
   891.7   774.2  1124.3  786.68  1143.8  788.48  1250.8  807.91  1445.2  839.43
  1668.9  906.52  1717.5  917.84  1746.7  923.43  1766.1  925.28  1814.7   923.6
#Mann= 3 , 0 , 0
       0    .055       0   814.4    .045       0   853.1     .05       0
#XS Ineff= 2 , 0
          747.35  774.09
Permanent Ineff=
       F       F
Bank Sta=814.4,853.1
XS Rating Curve= 0 ,0
Exp/Cntr=0.3,0.1

Type RM Length L Ch R = 1 ,53323.4 ,73,72.9,73
XS GIS Cut Line= 6
      1524863.83      291570.872     1524329.687      291374.749
      1524225.52      291316.156     1524162.586       291229.35
     1523839.235      291042.718     1523264.148      291372.579
#Sta/Elev= 30
       0  842.78   127.5  821.13   225.6  801.51   294.3  789.42     363  780.34
   392.4  779.42   431.7  773.89   461.1  772.63   559.2  770.48   633.4  770.84
   688.5  769.35     747  770.54   776.2   770.3   795.8  769.83   813.8  767.71
     832  766.79   850.1   769.8   877.2  772.27   914.9  771.86     954  772.84
  1061.7  772.67  1110.6  773.45  1169.3  775.67  1383.8  786.53  1442.3  790.84
  1510.5   799.4  1559.3  804.62  1637.3  806.93  1734.8  813.55  1832.3  824.18
#Mann= 3 , 0 , 0
       0     .08       0   813.8    .045       0   850.1     .05       0
#XS Ineff= 2 , 0
             676  774.66
Permanent Ineff=
       F       F
Bank Sta=813.8,850.1
XS Rating Curve= 0 ,0
Exp/Cntr=0.3,0.1

Type RM Length L Ch R = 1 ,53250.4 ,608.2,585.2,561.7
XS GIS Cut Line= 6
     1524894.212      291505.768     1524360.069      291309.645
     1524255.902      291251.051      1524109.49      291109.935
      1523828.24      290971.046      1523203.24      291325.212
#Sta/Elev= 30
       0  810.22     157     786   196.2  781.58   235.4  778.86   313.9  776.05
     363  779.02   431.7  780.79   461.1   780.4   500.3  779.06   587.4  774.49
     661  773.98     708  772.33   756.8   772.6     786  770.82   818.5767.5325
     832  766.48  845.02767.3127   877.2  770.78   914.9  771.74     964  771.74
    1062  770.39  1101.2   770.8  1228.7  775.34    1396  782.14    1455  784.95
  1494.4  787.47  1632.2  799.18  1760.1  803.36    1829   807.7  1927.4  815.57
#Mann= 3 , 0 , 0
       0    .055       0   818.5    .045       0  845.02     .05       0
Bank Sta=818.5,845.02
XS Rating Curve= 0 ,0
Exp/Cntr=0.3,0.1

Type RM Length L Ch R = 1 ,52665.2 ,1188.6,1163.6,1137
XS GIS Cut Line= 4
     1524839.525      290265.317      1524332.58      290525.733
     1524110.358      290633.372     1522908.969      291449.344
#Sta/Elev= 30
       0 1015.62   117.9 1010.47   157.2 1000.52   206.4  979.67   265.3  959.47
   314.4  932.69   343.9  919.15   432.4  892.82   491.3  868.56   550.3  839.53
   588.9  818.17   607.9  805.28   636.4  781.31   645.9  775.66   683.9  767.18
   702.9  765.68   712.4  766.23   750.4  769.29   788.4  769.79   934.6   768.1
  1140.7  768.66  1209.4  771.33  1297.7   778.4    1386  780.13  1621.5  788.47
  1758.9  795.42  1984.6  810.92  2082.7  822.52  2220.1  835.04  2269.1  840.89
#Mann= 3 , 0 , 0
       0      .1       0   683.9    .045       0   712.4     .05       0
Bank Sta=683.9,712.4
XS Rating Curve= 0 ,0
Exp/Cntr=0.3,0.1

Type RM Length L Ch R = 1 ,51501.6 ,1315.1,1307.7,1298.3
XS GIS Cut Line= 4
     1523169.386        289879.9      1523145.08       290161.15
     1523148.552      290393.789     1522947.163      291341.705
#Sta/Elev= 30
       0  974.97    29.2  965.19    38.9  961.05   116.8  923.86   194.7  887.86
   243.4  861.92   350.2  803.72   369.6  791.99   388.9     779   398.6  774.24
     418  766.43   427.7  762.97   437.4  761.59   447.1  762.64   476.2  765.69
   544.3  767.87   720.5  768.16   730.3  768.97   740.1     771   779.3  780.78
     789  782.11   828.2  784.62     838  784.99   847.8  784.46   867.4  780.97
   877.1  780.18   886.9  780.45  1249.1  798.97  1376.4   810.9    1484  823.96
#Mann= 3 , 0 , 0
       0      .1       0     418    .045       0   447.1     .05       0
Bank Sta=418,447.1
XS Rating Curve= 0 ,0
Exp/Cntr=0.3,0.1

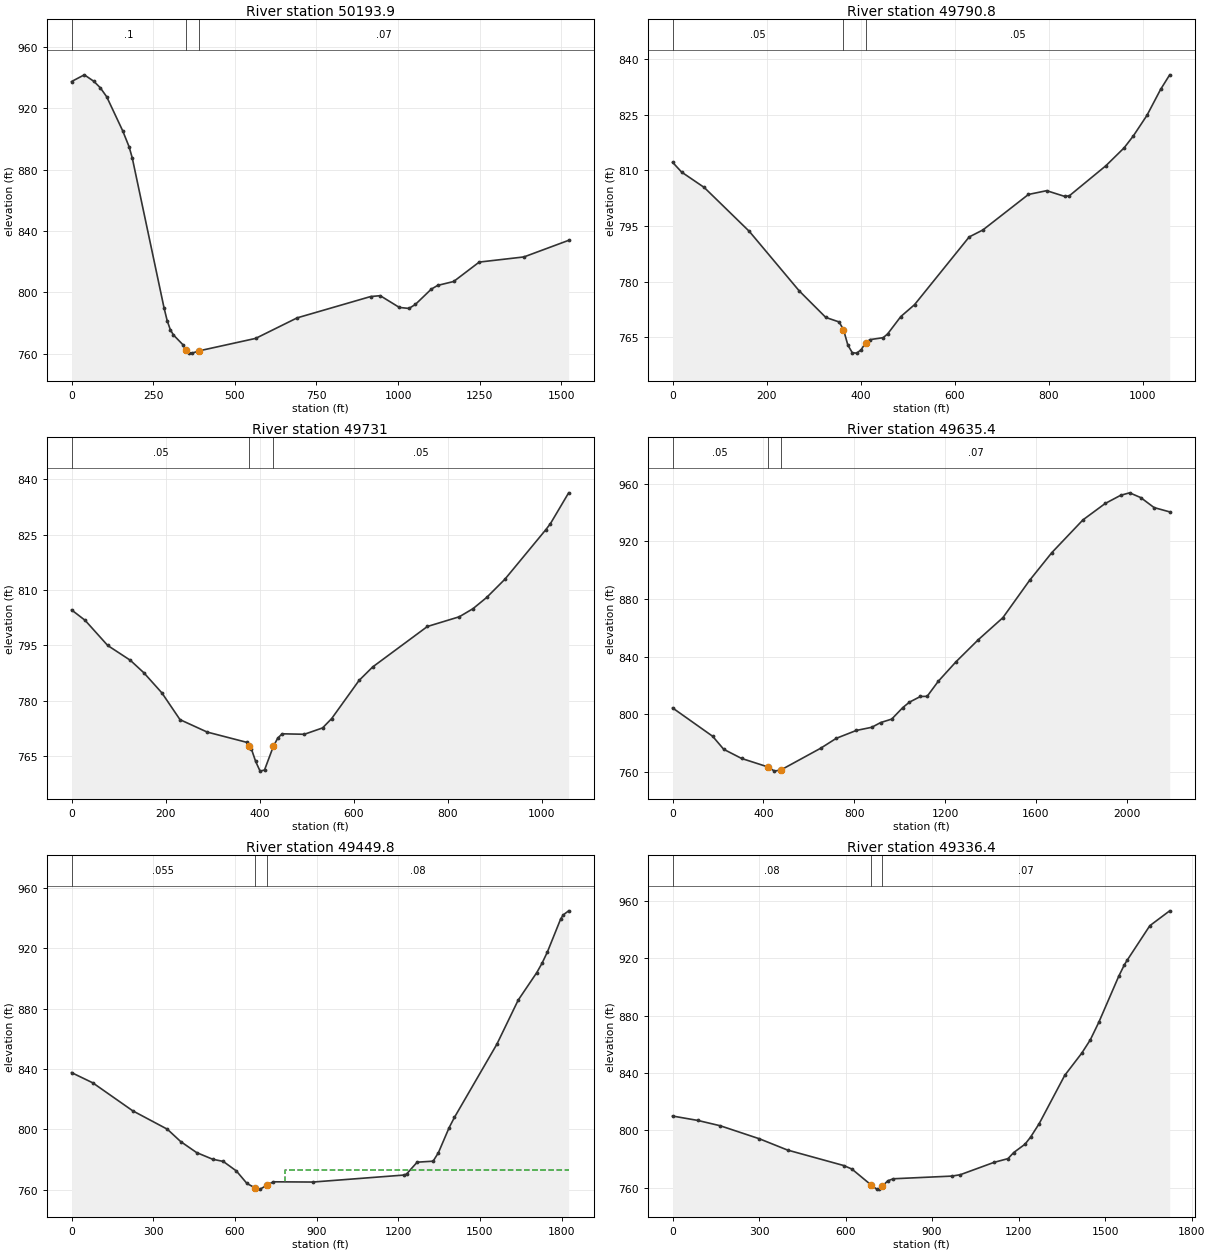
Type RM Length L Ch R = 1 ,50193.9 ,418.5,403.2,387.8
XS GIS Cut Line= 4
     1521756.083      290198.064     1521877.719      290421.567
     1521961.052      290616.011     1522405.497      291574.344
#Sta/Elev= 30
       0   937.3    39.2  941.68    68.5  937.43    88.1  933.26   107.7   927.4
   156.6  905.28   176.2   894.9     186  887.56   283.3  789.97   292.9  781.61
   302.5  775.74   312.2  772.25     341  765.96   350.6  762.41   360.2  760.61
   369.8  760.45   389.1  761.86   563.8  770.04     691  783.42     916   797.3
   945.3  797.86    1004   790.2  1033.3  789.56  1052.9  792.14  1101.8  802.14
  1121.4  804.56  1170.3   807.1  1248.5  819.74  1385.4  823.09  1522.4   833.9
#Mann= 3 , 0 , 0
       0      .1       0   350.6    .045       0   389.1     .07       0
Bank Sta=350.6,389.1
XS Rating Curve= 0 ,0
Exp/Cntr=0.3,0.1

Type RM Length L Ch R = 1 ,49790.8 ,59.5,59.7,59.5
XS GIS Cut Line= 4
      1521461.92      290610.803     1521647.684      290831.289
     1521821.295      290924.171     1522185.879      291364.275
#Sta/Elev= 30
       0   812.2    19.2  809.55    67.3   805.4   163.4  793.52   269.1  777.52
   325.8  770.33   353.9  769.13   363.3  767.07   372.7  762.85   382.1  760.82
   391.4  760.71   400.8  761.61   410.2  763.49   419.6  764.35   447.7  764.88
   457.1  765.88   485.2  770.58   514.3  773.77   630.5  792.05   659.6  793.93
   756.4  803.51   795.2  804.53   833.9  802.97   843.6  803.17   921.1  811.26
   959.8  816.08   979.2  819.26  1008.3  824.83  1037.3  831.83  1056.7  835.78
#Mann= 3 , 0 , 0
       0     .05       0   363.3    .045       0   410.2     .05       0
Bank Sta=363.3,410.2
XS Rating Curve= 0 ,0
Exp/Cntr=0.3,0.1

Type RM Length L Ch R = 1 ,49731   ,84.6,95.6,107.1
XS GIS Cut Line= 4
     1521409.837      290648.997     1521595.601      290869.483
     1521769.212      290962.365     1522133.795      291402.469
#Sta/Elev= 30
       0  804.61    28.8  801.79    76.9  794.97   124.9  790.97   153.8  787.57
   192.2  782.11   230.6  774.88   288.3  771.52   372.7  768.73  377.69767.8276
   382.1  767.03   391.4  763.56   400.8  760.94   410.2  761.24     429  767.64
   438.3  769.88   447.7  771.05   494.9  770.92   533.6  772.64     553  775.18
   611.1  785.49   640.2  789.16   756.4  800.11   824.2  802.74   853.3  804.93
   882.4  807.97   921.1   812.9  1008.3  826.35    1018  827.98  1056.7  836.31
#Mann= 3 , 0 , 0
       0     .05       0  377.69    .045       0     429     .05       0
Bank Sta=377.69,429
XS Rating Curve= 0 ,0
Exp/Cntr=0.3,0.1

Type RM Length L Ch R = 1 ,49635.4 ,184.1,185.6,184.3
XS GIS Cut Line= 6
     1521362.962       290638.58     1521592.129      290931.983
     1521675.462      291060.455     1521818.691      291305.247
     1521948.289      291599.787     1522132.226      292641.973
#Sta/Elev= 30
       0  804.46   176.4  784.81   225.3  775.77   303.7  769.44   420.2  763.52
   448.9  760.63   477.6  761.49   652.6  776.53     721  783.37     809  788.82
   877.3  791.02   916.3  794.29   965.1   796.7  1013.8  804.66  1043.1  808.43
  1091.8   812.4  1121.1  812.46  1170.1   822.9  1248.5  836.48  1346.6  851.76
  1454.5  866.97  1572.2  892.86  1670.2  912.09  1807.3  934.79  1905.2  946.15
  1973.8  951.87    2013  953.54  2061.9  950.22  2120.7   943.3  2189.2  940.33
#Mann= 3 , 0 , 0
       0     .05       0   420.2    .045       0   477.6     .07       0
Bank Sta=420.2,477.6
XS Rating Curve= 0 ,0
Exp/Cntr=0.3,0.1

Type RM Length L Ch R = 1 ,49449.8 ,107.4,113.4,118.7
XS GIS Cut Line= 5
     1521259.663      290296.567     1521391.608      290827.817
     1521523.552      291140.317     1521563.483      291471.914
     1521200.636      291956.289
#Sta/Elev= 30
       0  837.66    78.2  830.85   224.8  812.31   351.9   800.1   400.8  791.92
   459.4   784.6   518.1  780.19   557.1  778.74   605.5   772.4   644.3   764.1
   673.4  761.24   692.8  760.35  716.73762.8478   741.2  765.21   886.6  765.05
  1220.6  769.68  1230.4  770.35  1269.4  778.23    1328  778.89  1347.5  784.55
  1386.5  801.02  1406.1  807.88  1562.2  856.52  1640.3   885.7  1708.7     904
  1728.2  910.27  1747.7  917.68  1796.5   939.6  1806.3  942.34  1825.8  944.98
#Mann= 3 , 0 , 0
       0    .055       0   673.4    .045       0  716.73     .08       0
#XS Ineff= 2 , 0
                          782.61          772.99
Permanent Ineff=
       F       F
Bank Sta=673.4,716.73
XS Rating Curve= 0 ,0
Exp/Cntr=0.3,0.1

Type RM Length L Ch R = 1 ,49336.4 ,569,588.3,607.6
XS GIS Cut Line= 5
     1521152.025      290253.164     1521311.747      290824.344
     1521377.719      291063.928     1521446.295      291378.164
     1521106.886      291824.344
#Sta/Elev= 30
       0  810.03    87.5  806.97   165.3  803.26   301.4  794.17   398.6  786.35
   593.1  775.59   621.8  773.13   688.7  762.01   707.8  759.14   717.3  759.44
   726.9  761.09     746  764.88   765.1  766.35   968.3  768.21   997.5  769.16
  1114.5  777.76  1163.2  780.38  1182.9   784.6  1222.2  790.43  1241.9  795.49
  1271.4  804.79  1359.9  838.35  1418.9  853.82  1448.4  863.04    1478   875.3
  1546.8  907.21  1566.5  915.26  1576.3  918.49    1655  942.56  1723.8   952.9
#Mann= 3 , 0 , 0
       0     .08       0   688.7    .045       0   726.9     .07       0
Bank Sta=688.7,726.9
XS Rating Curve= 0 ,0
Exp/Cntr=0.3,0.1

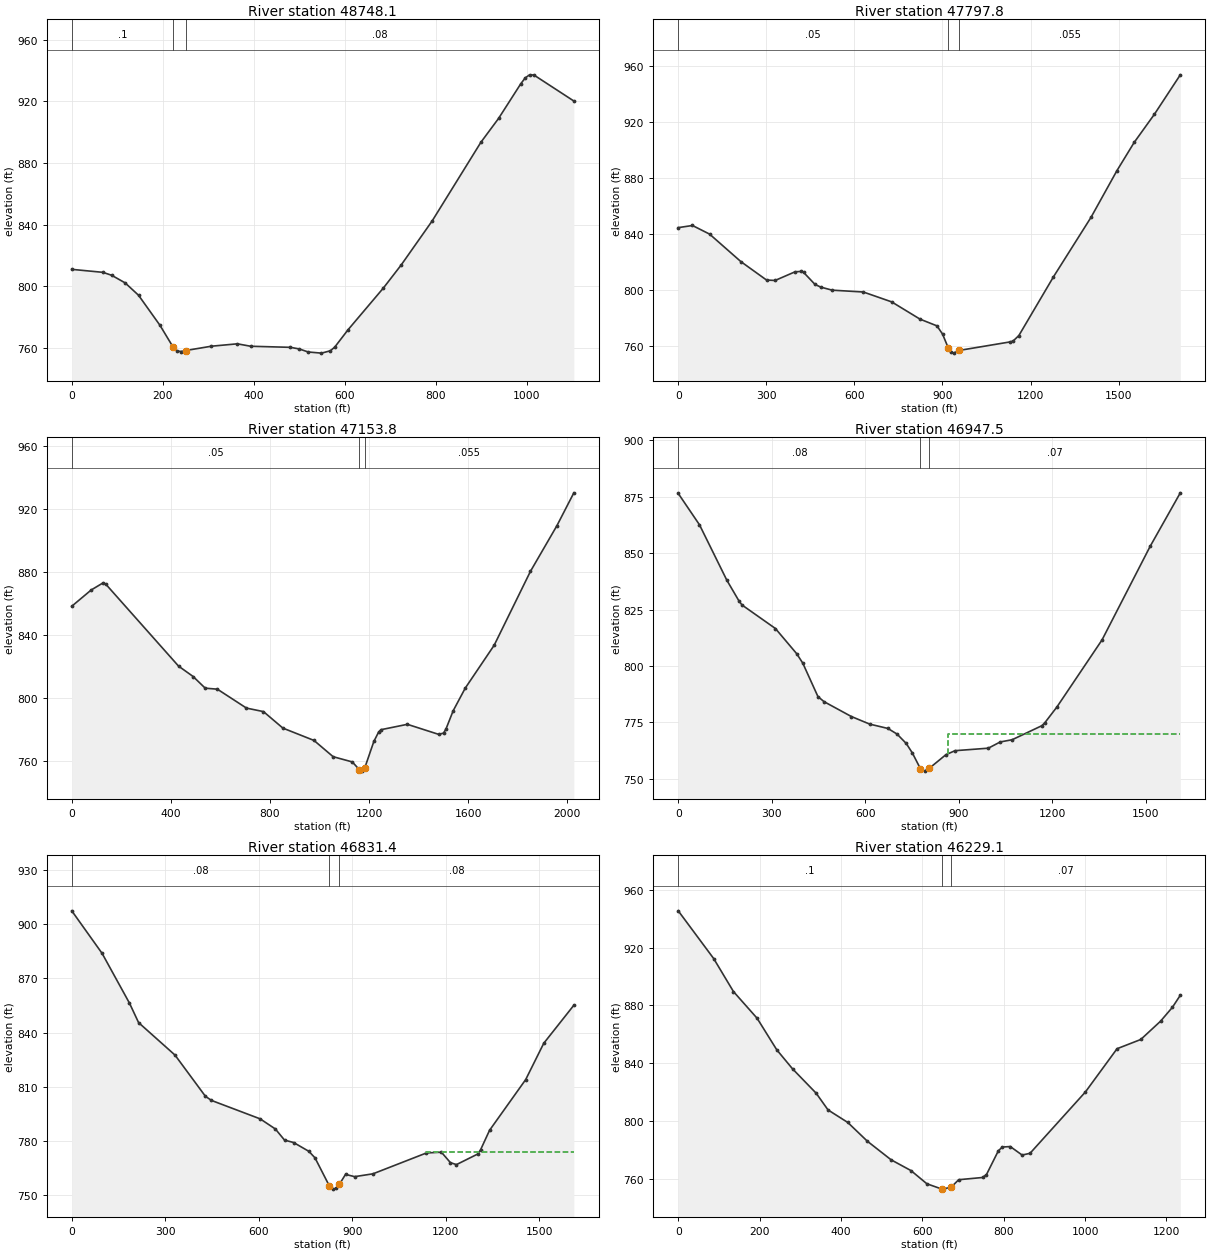
Type RM Length L Ch R = 1 ,48748.1 ,937.8,950.3,962.2
XS GIS Cut Line= 4
       1521136.4      290245.351      1521113.83      290390.317
     1521013.136      290560.455     1520592.997        291192.4
#Sta/Elev= 30
       0  810.99    68.5  809.05      88   807.1   117.4  802.18   146.7  794.19
   193.8  774.68     222  760.86   231.4  758.02   240.9  757.64   250.3   758.3
   306.8  761.11   363.9  762.66   393.1  761.08   480.6  760.38   500.1  759.32
   519.5  757.36   548.7  756.62   568.2  758.13   577.9  760.55   607.1  771.78
   684.9  798.92   723.8  813.79     792  842.43     899  893.44   937.9  908.94
   986.5  931.34   996.3   935.2    1006  937.23  1015.7  937.08  1103.3  920.23
#Mann= 3 , 0 , 0
       0      .1       0     222    .045       0   250.3     .08       0
Bank Sta=222,250.3
XS Rating Curve= 0 ,0
Exp/Cntr=0.3,0.1

Type RM Length L Ch R = 1 ,47797.8 ,629.7,644,657.5
XS GIS Cut Line= 5
     1521419.386      289675.039     1520867.302      289709.761
     1520558.275      289706.289      1520395.08      289803.511
     1520016.608      290341.705
#Sta/Elev= 30
       0  844.67    48.5  846.19   106.8  840.05   213.5  820.42   300.8  807.29
     330     807   397.9  813.17   417.3  813.42     427  812.76   465.8  804.18
   485.2  802.28   524.1  800.08   630.4  798.77     727  791.72   823.6  779.41
   881.2  774.62   900.2  768.78   919.2  759.15   928.7  755.68   938.2  755.18
   957.2  757.12  1130.7  763.19  1140.6  763.81  1160.2  767.72    1278  809.57
  1405.7  851.92  1494.1  885.26    1553  905.44  1621.8  925.49  1710.1  953.63
#Mann= 3 , 0 , 0
       0     .05       0   919.2    .045       0   957.2    .055       0
Bank Sta=919.2,957.2
XS Rating Curve= 0 ,0
Exp/Cntr=0.3,0.1

Type RM Length L Ch R = 1 ,47153.8 ,198.8,206.4,212.9
XS GIS Cut Line= 4
     1521273.552      289084.761     1520461.052      289341.705
     1519950.636      289300.039     1519374.247      289626.428
#Sta/Elev= 30
       0  858.08    78.4  868.39   127.3     873   137.1  872.12     431   820.1
   489.8   813.5   538.7  806.09   587.7  805.46   705.2  793.45   773.8  791.23
   852.2  780.76   977.8  772.93  1055.1  762.61  1132.4  759.29  1161.4   754.3
    1171  753.46  1182.6  755.46  1219.3  772.26  1238.7  778.26  1248.3  779.75
  1354.6  783.16  1481.2  776.78  1500.6   777.6  1510.4  780.13  1539.6  791.76
  1588.3  806.12  1705.2  833.36  1851.3  880.16  1958.5  909.23  2026.7  930.04
#Mann= 3 , 0 , 0
       0     .05       0  1161.4    .045       0  1182.6    .055       0
Bank Sta=1161.4,1182.6
XS Rating Curve= 0 ,0
Exp/Cntr=0.3,0.1

Type RM Length L Ch R = 1 ,46947.5 ,114.6,116,118
XS GIS Cut Line= 5
     1520874.247      289025.733      1520363.83      289188.928
     1519954.108      289056.983     1519756.191      289025.733
      1519363.83      289234.067
#Sta/Elev= 30
       0  876.45    68.2  862.55   155.9     838   194.9  828.79   204.6  827.01
   311.8  816.58     380  805.43   399.5  801.26   448.2  786.42   467.7  784.17
   555.4  777.58   614.1  774.22   672.8  772.28   702.2  769.78   731.5  765.64
   751.1  761.44   777.1 754.436   790.2  753.37  805.01754.5728   858.7  760.64
     888  762.43   994.9  763.54  1033.1   766.3  1071.3  767.28  1166.7  773.51
  1176.3  774.83    1215   781.8  1359.8  811.54  1514.4  853.07  1610.9  876.72
#Mann= 3 , 0 , 0
       0     .08       0   777.1    .045       0  805.01     .07       0
#XS Ineff= 2 , 0
                          864.51          769.76
Permanent Ineff=
       F       F
Bank Sta=777.1,805.01
XS Rating Curve= 0 ,0
Exp/Cntr=0.3,0.1

Type RM Length L Ch R = 1 ,46831.4 ,637.7,602.3,567
XS GIS Cut Line= 5
      1520895.08      288931.983     1520384.663      289095.178
     1519974.941      288963.233     1519777.025      288931.983
     1519384.663      289140.317
#Sta/Elev= 30
       0  907.33    97.4  883.78   185.1   856.3   214.4  845.52   331.3  827.55
   428.7   804.8   448.2  802.49   604.4   792.3   653.3  786.69   682.6  780.56
     712  779.19   760.9  774.32   780.4  770.73  826.13755.3209   839.1  753.44
   848.9  753.94   858.7  756.09   878.3  761.59   907.6  760.34   966.3   761.9
  1138.1  773.45    1186  773.86    1215  768.06  1234.3     767  1301.9   772.8
  1311.5  775.14  1340.5  785.98  1456.4  814.02  1514.4   834.1  1610.9  855.12
#Mann= 3 , 0 , 0
       0     .08       0  826.13    .045       0   858.7     .08       0
#XS Ineff= 2 , 0
                         1137.42          773.96
Permanent Ineff=
       F       F
Bank Sta=826.13,858.7
XS Rating Curve= 0 ,0
Exp/Cntr=0.3,0.1

Type RM Length L Ch R = 1 ,46229.1 ,949.4,940.4,930.1
XS GIS Cut Line= 4
     1520033.969       288223.65      1519676.33      288605.594
     1519568.691      288813.928     1519283.969      289195.872
#Sta/Elev= 30
       0  945.59    87.2  912.47   135.7  889.65   193.8  871.16   242.2  849.26
     281  836.06   339.1  819.17   368.2   807.6   416.7  798.92   465.1  785.86
   523.2  773.04   572.1  765.56   611.2  756.41  647.66752.7855   650.3  752.71
   670.9754.1065   689.4  759.24     748  760.77   757.7  762.83   786.9   779.3
   796.6  781.87   816.1  782.23   845.2  776.34   864.7  777.53  1000.8  820.04
  1078.6  850.02  1136.9  856.42  1185.5  869.09  1214.7  878.73  1234.1  887.08
#Mann= 3 , 0 , 0
       0      .1       0  647.66    .045       0   670.9     .07       0
Bank Sta=647.66,670.9
XS Rating Curve= 0 ,0
Exp/Cntr=0.3,0.1

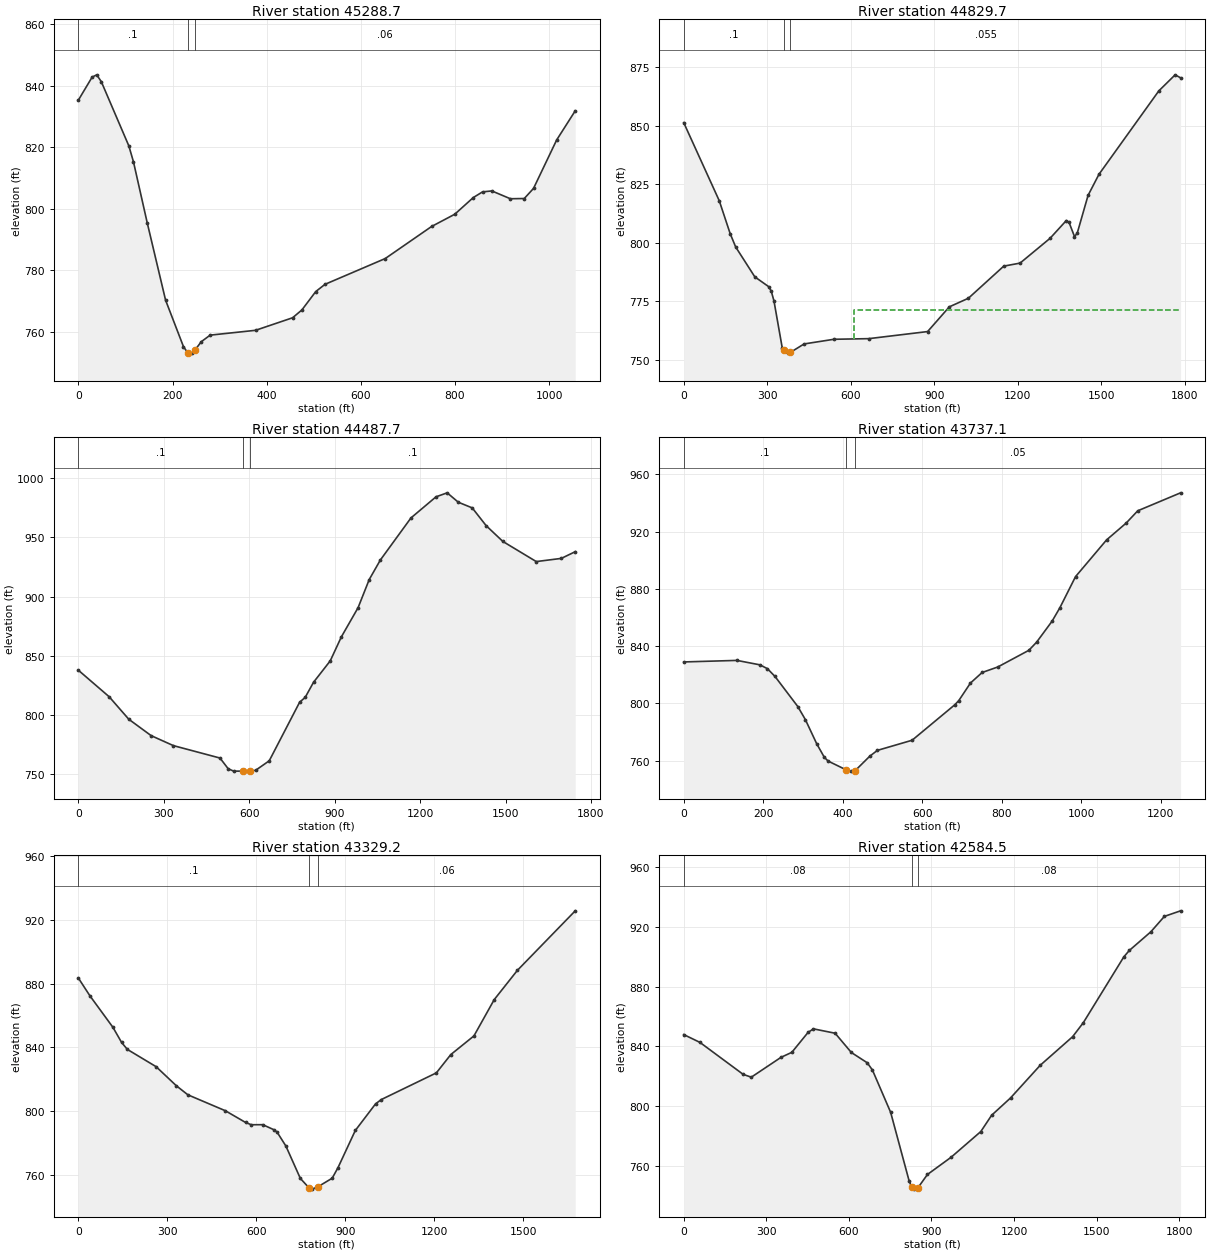
Type RM Length L Ch R = 1 ,45288.7 ,466.5,459.1,451.4
XS GIS Cut Line= 4
     1518975.701       287914.21     1518961.812      288108.654
     1518954.867      288240.599     1519048.617      288962.821
#Sta/Elev= 30
       0   835.4    29.2  842.88      39  843.62    48.7  841.39   107.2   820.5
     117  815.33   146.2  795.51   185.2  770.35   223.2  755.23   232.7  753.11
   242.1  753.11   248.3  754.23     261  756.82   279.9  758.96   376.3  760.53
     455  764.61   474.7  767.14   504.2  773.13   523.9  775.49   651.8  783.87
   750.3   794.3   799.5  798.28   838.8   803.7   858.5  805.55   878.2  805.86
   917.6  803.32   947.1  803.39   966.8  806.68    1016  822.45  1055.4  831.92
#Mann= 3 , 0 , 0
       0      .1       0   232.7    .045       0   248.3     .06       0
Bank Sta=232.7,248.3
XS Rating Curve= 0 ,0
Exp/Cntr=0.3,0.1

Type RM Length L Ch R = 1 ,44829.7 ,320.6,342,362
XS GIS Cut Line= 5
     1518656.256      287962.821     1518524.312      288181.571
     1518593.756      288407.265     1518704.867      288785.738
     1518715.284      289685.043
#Sta/Elev= 30
       0  851.29   127.7  817.89     167   803.8   186.7  798.12   255.5  785.34
   304.7   781.2   314.5  779.26   324.3  775.05   353.8  755.13  359.12753.9424
   373.5  752.73   383.4  753.05   432.6  756.66   539.7  758.65   664.8  758.92
   876.4  761.95   954.5  772.53  1022.9  776.19    1150  789.93  1208.6  791.22
  1316.2   801.8  1374.8  809.42  1384.6  808.66  1404.2  802.58  1413.9  803.97
    1453  820.18  1492.1  829.18  1707.2  864.86  1765.9  871.73  1785.4  870.45
#Mann= 3 , 0 , 0
       0      .1       0  359.12    .045       0   383.4    .055       0
#XS Ineff= 2 , 0
                          612.04          770.98
Permanent Ineff=
       F       F
Bank Sta=359.12,383.4
XS Rating Curve= 0 ,0
Exp/Cntr=0.3,0.1

Type RM Length L Ch R = 1 ,44487.7 ,724.5,750.6,776.7
XS GIS Cut Line= 4
     1518607.645      287931.571     1518409.729      288188.515
     1518184.034      288511.432      1517708.34      289421.154
#Sta/Elev= 30
       0  837.83   108.1  815.46   176.9   796.5   255.5  782.65   333.9   774.2
   497.3  763.74   526.1  754.72   545.3   752.7   577.6   752.7     603   752.7
   622.2  753.35   670.3  761.43     777  810.85   796.5  814.92   825.8  827.66
   884.5  845.74   923.6     866   982.3  890.63  1021.4  914.36  1060.5  930.84
    1168  966.34    1256  984.16  1295.2  987.52  1334.3  979.58  1383.1  974.82
    1432  959.83  1490.7   946.5    1608  929.51    1696  932.19  1744.9  937.86
#Mann= 3 , 0 , 0
       0      .1       0   577.6    .045       0     603      .1       0
Bank Sta=577.6,603
XS Rating Curve= 0 ,0
Exp/Cntr=0.3,0.1

Type RM Length L Ch R = 1 ,43737.1 ,424.7,408,390.7
XS GIS Cut Line= 4
     1518784.729      287841.293     1518524.312      287778.793
     1518281.256      287730.182     1517642.367      288091.293
#Sta/Elev= 30
       0  828.99   133.9  830.06   191.3  826.98   210.4  824.32   229.6  818.85
   286.9  797.86     306  788.71   334.6   771.8   353.6  762.42   363.2  759.78
  408.54753.6564   420.4  752.76  431.18753.0909     468   763.2   487.1  767.25
   574.4  774.32     682  799.13   691.8  802.01   721.2  814.27   750.5  821.62
   789.7  825.45   867.9  837.09   887.5  842.78   926.6  857.51   946.2   866.9
   985.4  888.54  1063.6  914.22  1112.6   925.9  1141.9  934.51  1249.6  947.06
#Mann= 3 , 0 , 0
       0      .1       0  408.54    .045       0  431.18     .05       0
Bank Sta=408.54,431.18
XS Rating Curve= 0 ,0
Exp/Cntr=0.3,0.1

Type RM Length L Ch R = 1 ,43329.2 ,740.8,744.6,747.9
XS GIS Cut Line= 4
     1518947.923       287070.46     1518329.867      287330.876
     1518138.895      287448.932     1517576.395      287990.599
#Sta/Elev= 30
       0  883.46    38.9  872.34   116.6  852.58   145.8  843.12   165.2  838.76
   262.4  827.91   330.5  815.97   369.4   810.3   495.7  800.33   563.8     793
   583.2  791.55   622.1  791.58     661   788.3   670.7   786.8     700  778.21
   748.8  757.91   778.1     752   787.8   751.2   807.3  752.58   856.2  758.05
   875.7  764.62   934.2  787.96  1002.6  804.65  1022.1  807.35  1207.6  824.05
  1256.4  835.53  1334.4  847.22  1402.8  869.96  1480.9  888.29  1676.1   925.6
#Mann= 3 , 0 , 0
       0      .1       0   778.1    .045       0   807.3     .06       0
Bank Sta=778.1,807.3
XS Rating Curve= 0 ,0
Exp/Cntr=0.3,0.1

Type RM Length L Ch R = 1 ,42584.5 ,428.5,415.5,402
XS GIS Cut Line= 5
     1518920.145      286639.904     1518291.673      286646.849
     1518159.729      286660.738     1517965.284      286740.599
     1517288.201       287226.71
#Sta/Elev= 30
       0  847.88    58.9  842.64     216   821.2   245.5  819.32   353.5  832.63
   392.8  835.98   451.7  849.34   471.4  851.71     550  848.78   608.9  835.87
   666.4  829.01   685.4  824.17   751.7  795.76   818.5     750   828.1   745.6
   837.6  744.28   849.7  744.91   885.4   754.1   971.4  765.66  1079.3  782.89
  1118.5  793.79  1187.1  805.38    1295  827.29  1412.7  846.44  1451.9  855.93
    1599  900.03  1618.6  904.24    1697  916.78  1746.1   927.1  1804.9  930.83
#Mann= 3 , 0 , 0
       0     .08       0   828.1    .045       0   849.7     .08       0
Bank Sta=828.1,849.7
XS Rating Curve= 0 ,0
Exp/Cntr=0.3,0.1

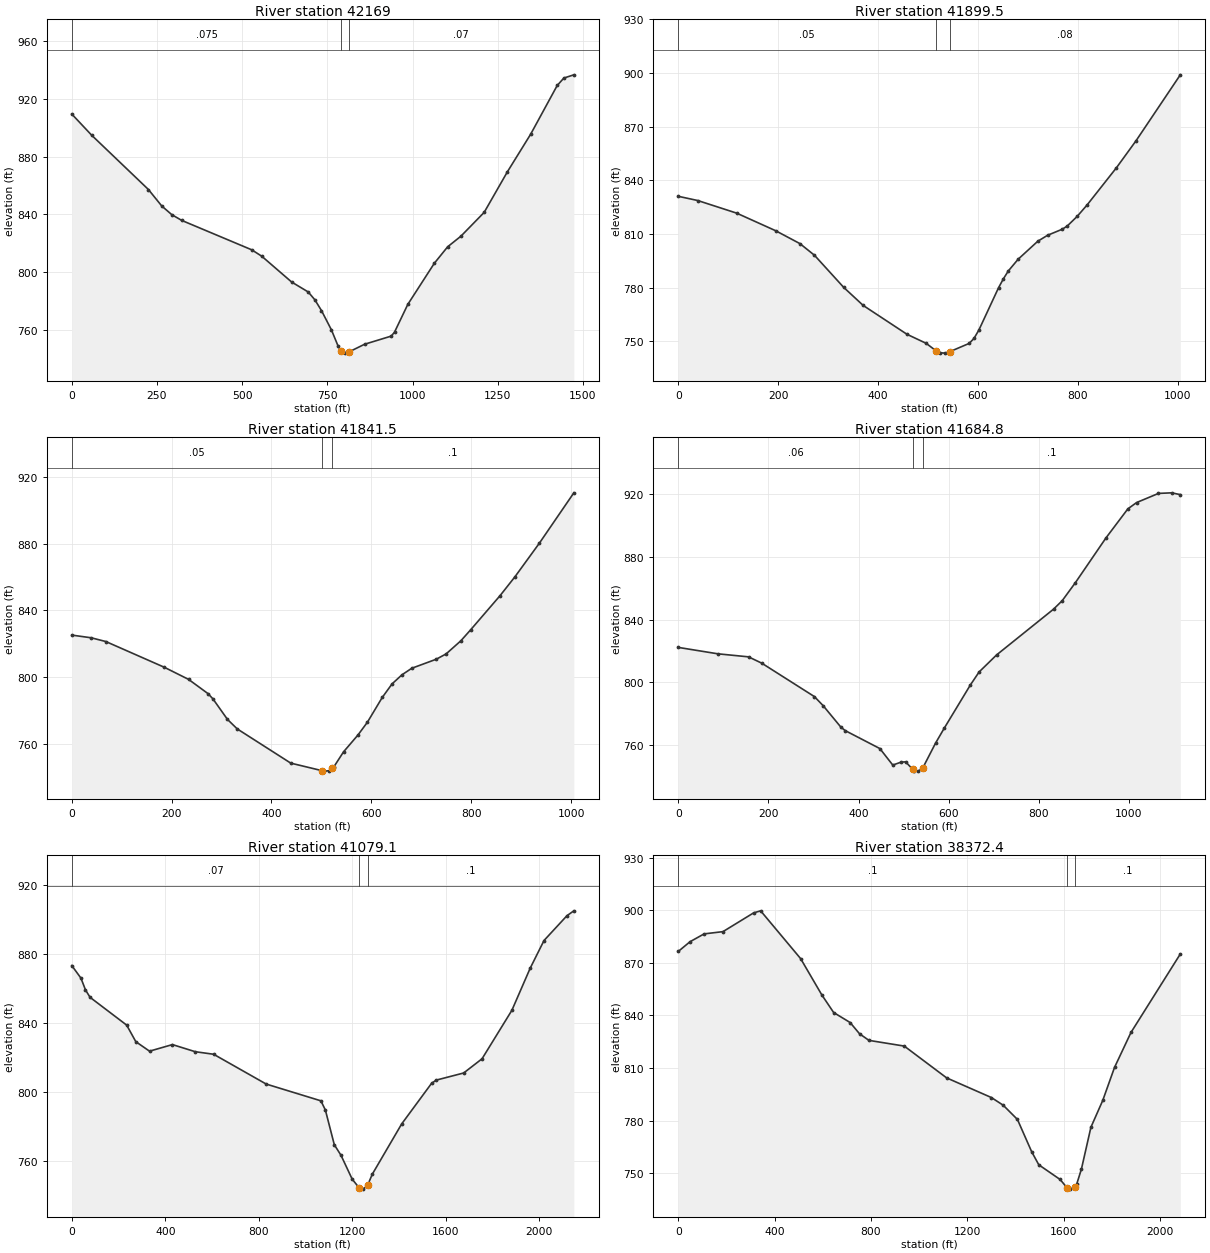
Type RM Length L Ch R = 1 ,42169   ,279,269.5,260
XS GIS Cut Line= 4
     1518263.895      285917.682     1517864.373      286306.354
     1517676.873      286591.076     1517312.289      287035.521
#Sta/Elev= 30
       0  909.48    58.7  894.72   224.9  857.17     264  845.75   293.4  839.75
   322.7  835.74     528  815.37   557.4  810.94     645  793.07   693.8  786.14
   713.2  780.74   732.7  773.25   761.9  759.86   781.4  748.68   791.2  744.92
   800.9  743.75     812  744.43   859.3  749.92   937.3  755.55     947  758.28
     986  777.53  1063.9  806.06  1102.9  817.45  1141.9  824.82  1210.1  841.32
  1278.3  869.47  1346.5   895.5  1424.4  929.28  1443.9  934.42  1473.2  936.66
#Mann= 3 , 0 , 0
       0    .075       0   791.2    .045       0     812     .07       0
Bank Sta=791.2,812
XS Rating Curve= 0 ,0
Exp/Cntr=0.3,0.1

Type RM Length L Ch R = 1 ,41899.5 ,61.5,58,56.6
XS GIS Cut Line= 4
     1517678.609       285964.34     1517480.692      286377.534
     1517456.387      286509.479     1517307.081      286894.896
#Sta/Elev= 30
       0  831.13      39  828.77     117  821.72     195   811.9   243.7  804.68
   272.9  798.16   331.4  780.21   370.4  770.12   458.2  753.98   496.5  748.94
   515.6  744.91   525.2  743.64   534.8  743.45   544.4  744.33   582.7  748.88
   592.3  751.65   602.2  756.38   641.5  779.98   651.4  785.07   661.2  789.42
   680.9  795.98   720.2  806.02   739.9  809.36   769.4  812.75   779.3  814.55
     799  819.89   818.7  826.22   877.7   847.1   917.1  862.25  1005.6  899.04
#Mann= 3 , 0 , 0
       0     .05       0   515.6    .045       0   544.4     .08       0
Bank Sta=515.6,544.4
XS Rating Curve= 0 ,0
Exp/Cntr=0.3,0.1

Type RM Length L Ch R = 1 ,41841.5 ,141.8,156.7,168.8
XS GIS Cut Line= 4
     1517623.053      285960.868     1517425.137      286374.062
     1517400.831      286506.007     1517251.525      286891.423
#Sta/Elev= 30
       0  825.16      39  823.54    68.2   821.3   185.2  805.88     234  798.58
   272.9  790.04   282.7  786.92   311.9  774.56   331.4  768.88   438.6  748.35
  501.42743.8055     506  743.55   515.6  743.81     521  745.18   525.2  746.25
   544.4  755.14   573.2  765.22   592.3  772.97   621.8  787.73   641.5  795.88
   661.2   801.3   680.9  805.25   730.1  810.69   749.8  813.88   779.3  821.74
     799  828.36     858  848.89   887.6  860.13   936.8  880.41  1005.6  910.51
#Mann= 3 , 0 , 0
       0     .05       0  501.42    .045       0     521      .1       0
Bank Sta=501.42,521
XS Rating Curve= 0 ,0
Exp/Cntr=0.3,0.1

Type RM Length L Ch R = 1 ,41684.8 ,606.7,605.7,605.1
XS GIS Cut Line= 4
     1517614.373      285865.382      1517392.15      286209.132
     1517281.039      286351.493     1516992.845      286788.993
#Sta/Elev= 30
       0  822.29    87.7  818.21   155.9  816.27   185.2  812.26   302.1  790.95
   321.6  785.14   360.6  771.58   370.3  769.32   447.3  757.86   475.9  747.36
   494.9  749.26   504.4  749.39  520.53744.5546   523.4  743.76   532.9  743.49
   542.7  745.63   570.9  761.36   589.9  770.74   648.1  798.38   667.5  806.66
   706.3  817.51   832.5  846.62   851.9  852.07     881   863.5   948.9  892.03
   997.4  910.51  1016.8  914.53  1065.3  920.35  1094.4  920.73  1113.8  919.59
#Mann= 3 , 0 , 0
       0     .06       0  520.53    .045       0   542.7      .1       0
Bank Sta=520.53,542.7
XS Rating Curve= 0 ,0
Exp/Cntr=0.3,0.1

Type RM Length L Ch R = 1 ,41079.1 ,2731.1,2706.7,2681.5
XS GIS Cut Line= 4
     1517759.974      284734.305     1517183.586         285585.
     1516989.141      285845.416      1516971.78      286640.555
#Sta/Elev= 30
       0  873.39    39.2  866.08    58.7  859.22    78.3   854.9   234.9  838.74
     274  829.11   332.7  823.59   430.6  827.42   528.5  823.27   606.8   821.8
   831.8  804.46  1065.8  794.71  1084.9  789.38  1123.2  769.16  1151.8  763.02
  1199.6  749.16  1228.3  744.29  1247.3  743.35  1266.5  745.87  1285.7  752.04
  1411.5   781.3  1539.1  804.85  1558.8  806.74  1676.6   810.9  1755.2  819.17
  1882.8  847.35  1961.3   871.9  2020.3  887.96  2118.4  902.38  2147.9  905.22
#Mann= 3 , 0 , 0
       0     .07       0  1228.3    .045       0  1266.5      .1       0
Bank Sta=1228.3,1266.5
XS Rating Curve= 0 ,0
Exp/Cntr=0.3,0.1

Type RM Length L Ch R = 1 ,38372.4 ,1181.5,1198.9,1214.7
XS GIS Cut Line= 4
     1515867.613      284942.639     1516468.308      286095.416
      1516690.53      286512.083     1516832.891      286789.861
#Sta/Elev= 30
       0  876.55    48.9  882.12   107.5   886.6   185.7  887.88   312.8  898.59
   342.1  899.77   508.2  872.45   596.2   851.7   645.1  841.69   713.5  835.97
   752.6  829.54   791.7  825.77   938.3  822.51  1114.2  804.34  1299.9  793.12
  1349.1  788.72  1408.1   780.6  1467.1  762.18  1496.7   754.7  1585.2  746.31
  1614.7  741.46  1624.6   740.8 1647.19742.0765  1654.1  743.64  1673.7  752.26
  1713.1  776.14  1762.3  791.49  1811.1  810.32  1879.4  830.29  2084.2  875.11
#Mann= 3 , 0 , 0
       0      .1       0  1614.7    .045       0 1647.19      .1       0
Bank Sta=1614.7,1647.19
XS Rating Curve= 0 ,0
Exp/Cntr=0.3,0.1

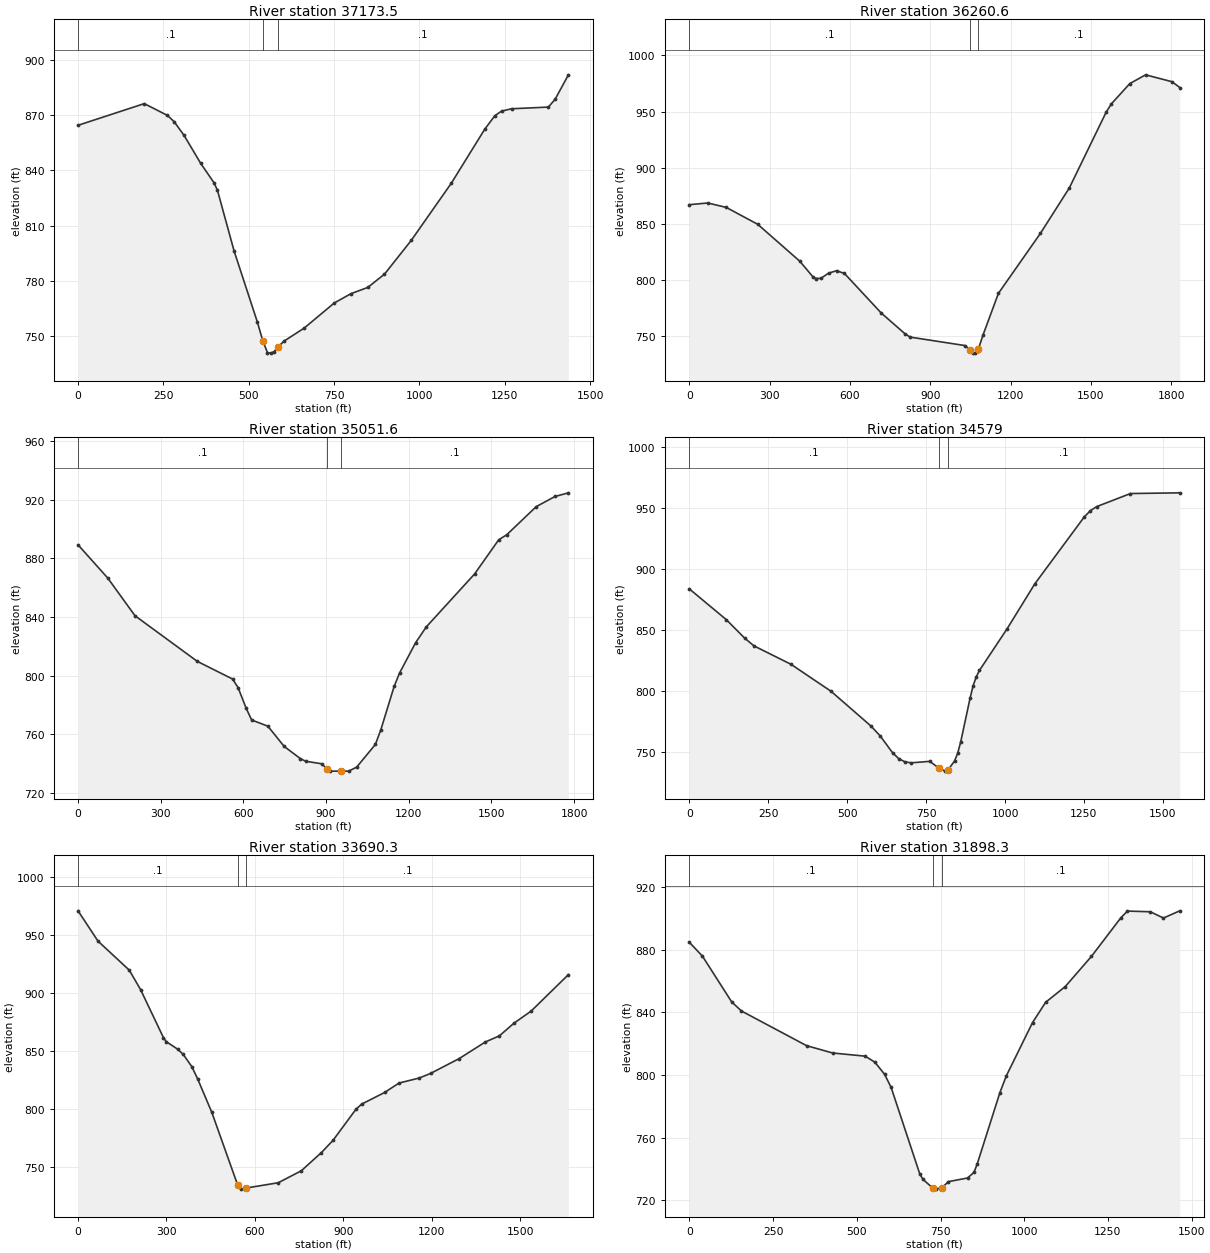
Type RM Length L Ch R = 1 ,37173.5 ,893.9,912.9,931.2
XS GIS Cut Line= 4
     1515808.586      285269.027     1515812.058      285598.889
     1515732.197      285921.805     1515607.197      286685.694
#Sta/Elev= 30
       0  864.53     194  876.29     262  869.87   281.4  866.51   310.5  859.07
   359.2  843.89   398.4   833.3   408.2  829.34   457.1  796.32   525.6  757.56
  541.35747.4049   554.9  741.17   564.7  740.86   574.5  741.64   584.3  743.98
   603.8  747.43   662.5  754.45   750.7  768.09   799.7  773.14   848.7  776.52
   897.7  783.72   976.1  802.05  1093.6  833.12  1191.6  862.45    1221  869.72
  1240.6  872.22    1270   873.5  1377.8  874.41  1397.4   878.6  1436.6  891.92
#Mann= 3 , 0 , 0
       0      .1       0  541.35    .045       0   584.3      .1       0
Bank Sta=541.35,584.3
XS Rating Curve= 0 ,0
Exp/Cntr=0.3,0.1

Type RM Length L Ch R = 1 ,36260.6 ,1206.6,1209,1211.3
XS GIS Cut Line= 4
     1515669.697       284991.25     1514981.329      285663.993
     1514797.301      285768.159     1514220.044         286085.
#Sta/Elev= 30
       0  867.23    68.8  868.73   137.5  864.81   255.4  849.76   412.5  816.92
   461.6  803.02   471.4  801.54   491.1  801.69   520.5  806.31     550  808.48
   579.5     806     717   770.8   805.4  752.41     825  749.39  1029.8  741.88
    1049  737.86  1058.6  735.64  1068.2  735.14  1077.9  737.43  1080.3  739.04
  1097.1  751.17  1154.8  788.35  1311.6  841.66  1419.7  882.09  1557.3  949.48
  1576.9  956.94  1645.7  974.94  1704.7  982.76    1803  976.67  1832.5  971.48
#Mann= 3 , 0 , 0
       0      .1       0    1049    .045       0  1080.3      .1       0
Bank Sta=1049,1080.3
XS Rating Curve= 0 ,0
Exp/Cntr=0.3,0.1

Type RM Length L Ch R = 1 ,35051.6 ,456.8,472.6,488.4
XS GIS Cut Line= 4
     1515423.169      284512.083     1514645.391      284761.215
     1514406.676      284869.722     1514050.773      285473.021
#Sta/Elev= 30
       0  889.18   108.2  866.42   206.6  840.82     433  809.65   560.9  797.61
   580.6   791.8   610.1  777.66   629.8  769.71   688.8  765.46   747.8  751.68
   806.9  743.31   826.4  741.53   884.7   739.8   904.1  735.96   913.8   734.8
   952.7   734.8   981.8   734.8  1010.9  737.51  1078.9  753.01  1098.4  762.86
    1147  792.59  1166.5  801.67  1224.8   822.4  1263.8  833.24  1438.9  869.31
  1526.4  892.64  1555.6  896.07  1662.6  915.26  1730.7  922.17  1779.4  924.67
#Mann= 3 , 0 , 0
       0      .1       0   904.1    .045       0   952.7      .1       0
Bank Sta=904.1,952.7
XS Rating Curve= 0 ,0
Exp/Cntr=0.3,0.1

Type RM Length L Ch R = 1 ,34579   ,894.2,888.8,882.1
XS GIS Cut Line= 4
     1515396.259      284413.993     1514723.516      284405.312
      1514476.12      284340.208     1513859.801      284236.041
#Sta/Elev= 30
       0  883.49     117  858.31   175.5  843.08   204.8   836.8   321.8  821.74
   448.5  799.67   575.3  771.13   604.5  763.04   643.6  749.27     663  744.47
   682.6  741.82   702.3  740.99   761.4  742.18   790.9  736.62   810.6  734.18
   820.4  735.44   840.1  742.53   849.9  748.72   859.7  758.27   889.3  793.99
   899.1  804.28   908.9  811.44   918.8  816.66  1006.8  850.92  1094.6  887.75
  1250.9  942.45  1270.4  947.61    1290  950.92  1397.4  961.68  1553.7  962.27
#Mann= 3 , 0 , 0
       0      .1       0   790.9    .045       0   820.4      .1       0
Bank Sta=790.9,820.4
XS Rating Curve= 0 ,0
Exp/Cntr=0.3,0.1

Type RM Length L Ch R = 1 ,33690.3 ,1799.9,1791.9,1782.1
XS GIS Cut Line= 4
     1515770.391      283789.861     1515287.752      283786.389
     1515051.641      283789.861     1514107.197      283831.527
#Sta/Elev= 30
       0  970.77    67.6   944.7   173.8  919.68   212.4   902.8   289.6  861.64
   299.2   858.1   337.9  851.64   357.2  847.05   386.1  836.55   405.4  826.27
   453.7  797.34   541.7  734.58   551.5  731.07   571.2  732.05   679.4  736.56
   757.8   746.9     826  762.58     865  772.98     943  799.83   962.4  804.28
  1040.4  814.32  1089.1  822.41  1157.4  826.73  1196.3  830.71  1293.8  843.55
  1381.5   857.7  1430.2  863.15    1479  873.92  1537.4  884.36  1664.2  915.84
#Mann= 3 , 0 , 0
       0      .1       0   541.7    .045       0   571.2      .1       0
Bank Sta=541.7,571.2
XS Rating Curve= 0 ,0
Exp/Cntr=0.3,0.1

Type RM Length L Ch R = 1 ,31898.3 ,692,692.9,694.4
XS GIS Cut Line= 4
     1515504.766      282217.812     1514905.808      282152.708
     1514654.072      282265.555      1514163.62      282586.736
#Sta/Elev= 30
       0  884.77    38.9  875.96   126.3  846.72   155.5  840.92   349.8   818.8
   427.6  814.11   524.8  812.08   553.9  808.25     583  800.51   602.5  792.12
   688.1  736.84   697.6   733.4   726.2  727.95   735.7  727.16   754.7  728.18
   773.7  731.94   830.8  734.27   849.8  737.85   859.3  743.02   927.2   788.7
   946.8  799.62  1024.9  833.56    1064  846.49  1122.6  856.54  1200.8  875.81
  1288.7  900.48  1308.3  904.74  1376.7   904.3  1415.8   900.3  1464.6   904.9
#Mann= 3 , 0 , 0
       0      .1       0   726.2    .045       0   754.7      .1       0
Bank Sta=726.2,754.7
XS Rating Curve= 0 ,0
Exp/Cntr=0.3,0.1