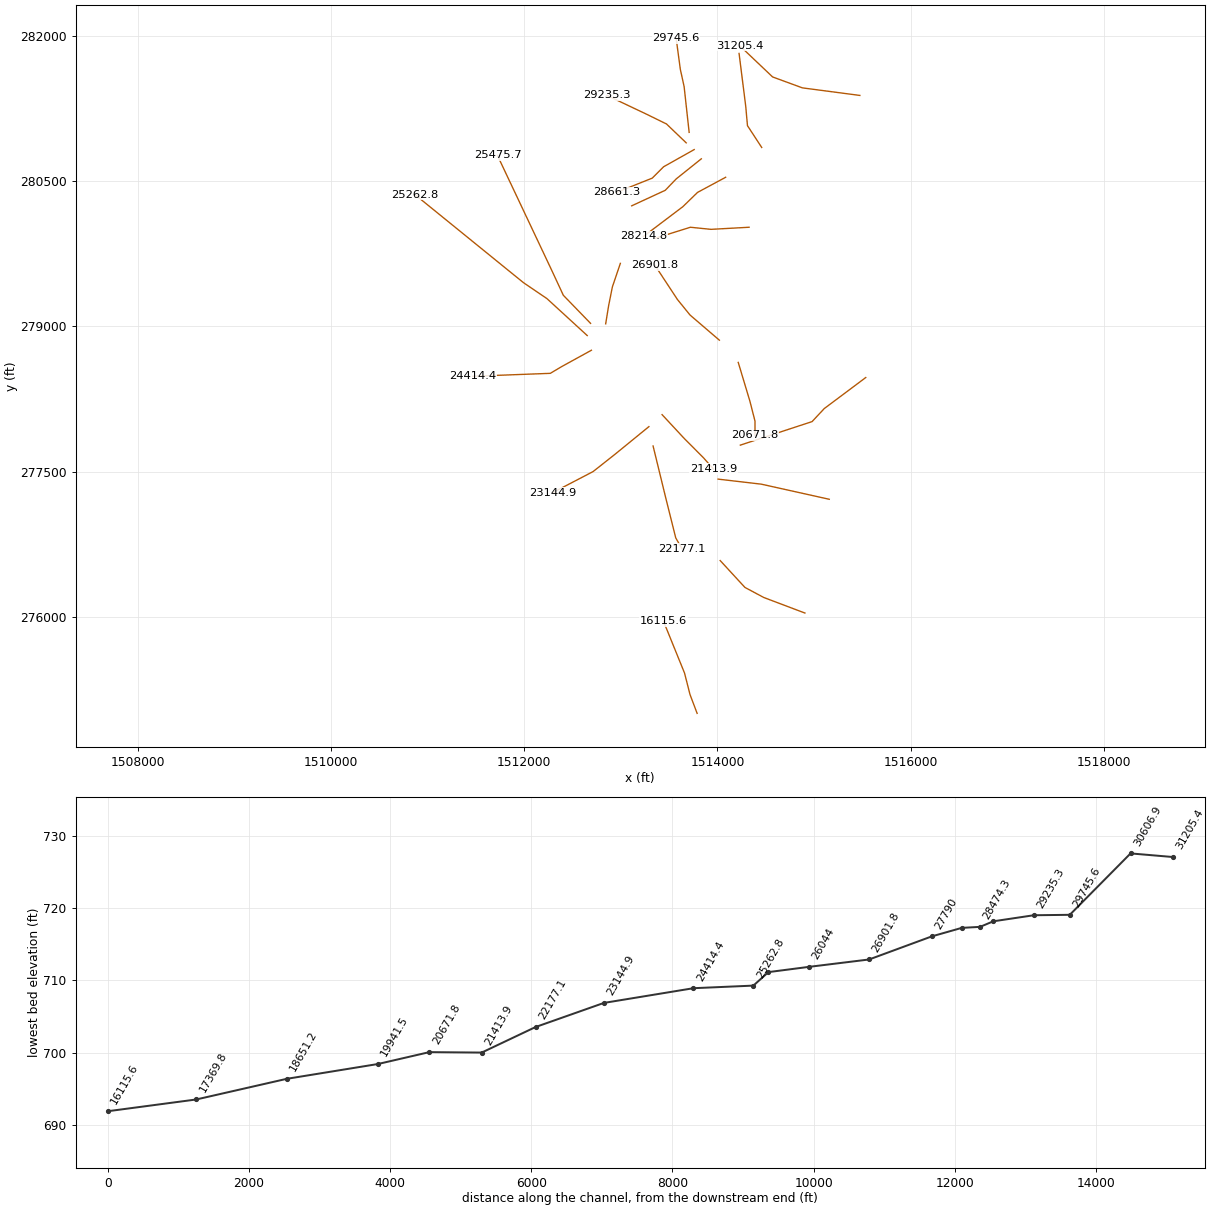
HEC-RAS study BNDSCR.prj: BNDSCR

--- BNDSCR.g01 (geometry) --- (continued)

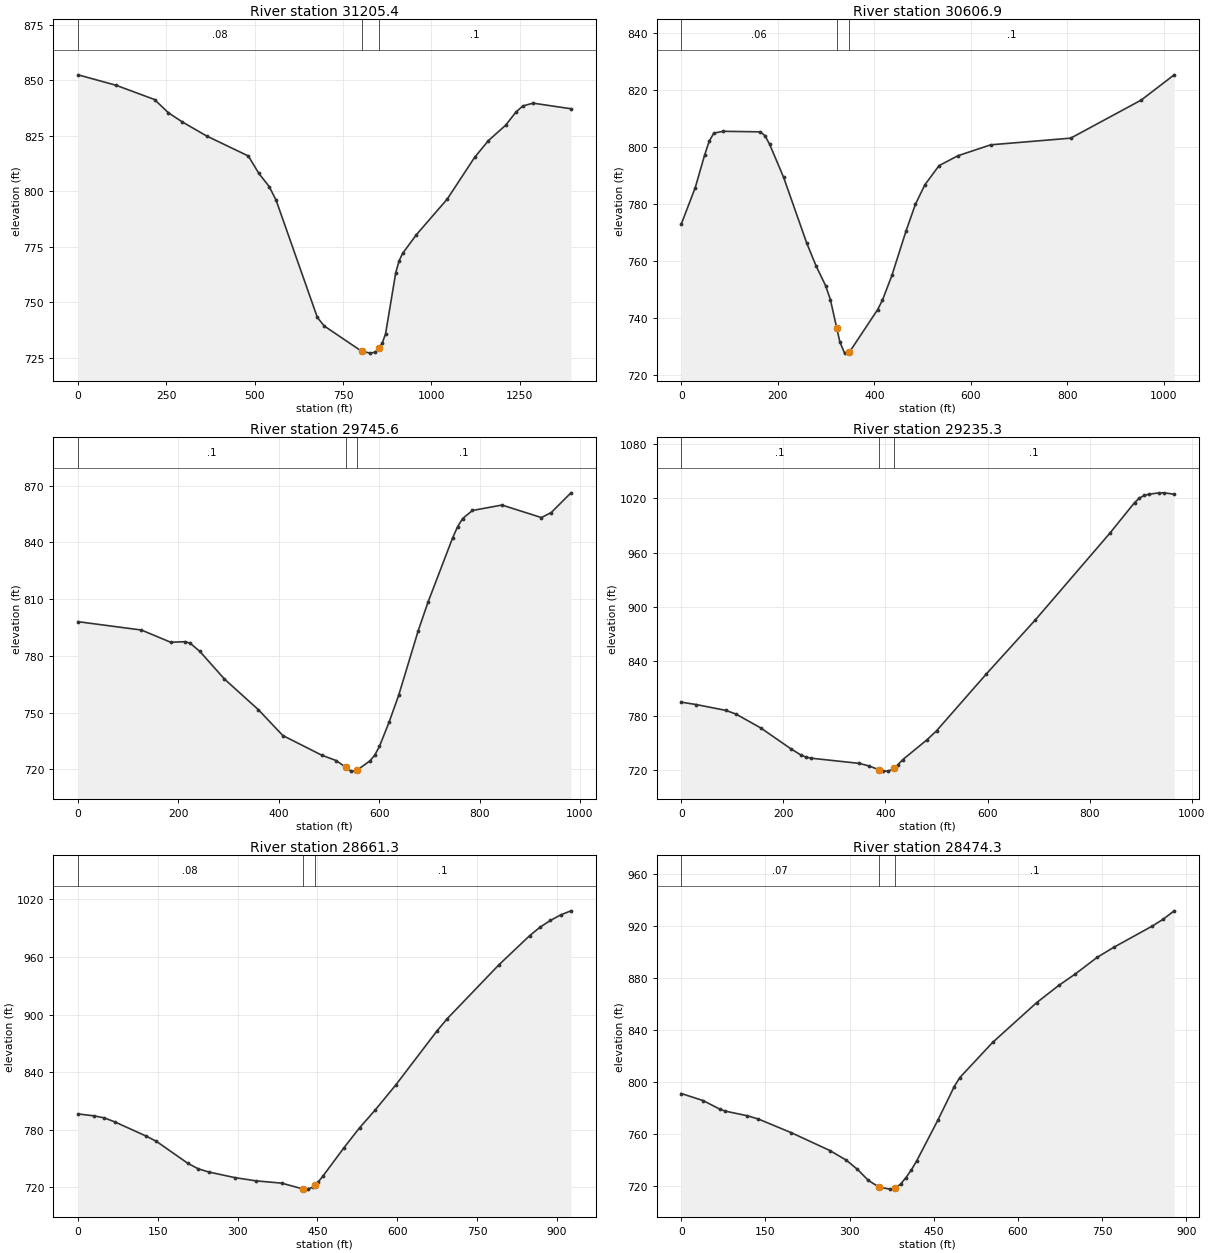
Type RM Length L Ch R = 1 ,31205.4 ,623.3,598.5,572.8
XS GIS Cut Line= 4
     1515474.384      281388.819     1514879.766      281466.944
     1514571.606      281579.791     1514233.065      281900.972
#Sta/Elev= 30
       0  852.52   108.2  847.78   216.3  841.39   255.6  835.42     295  831.29
   363.8  824.96   481.8  815.94   511.2  808.18   540.7  802.19   560.4     796
     677  743.22   696.2  739.37   802.4  727.94   827.1   727.1     841  727.58
   850.7   729.2   860.3   731.5     870  735.74   898.9  763.38   908.6   768.8
   918.2  772.02   957.1  780.44  1044.6  796.54  1122.3  815.38  1161.2   822.9
  1209.8  829.81    1239  835.73  1258.4   838.5  1287.6  839.75  1394.6  837.23
#Mann= 3 , 0 , 0
       0     .08       0   802.4    .045       0   850.7      .1       0
Bank Sta=802.4,850.7
XS Rating Curve= 0 ,0
Exp/Cntr=0.3,0.1

Type RM Length L Ch R = 1 ,30606.9 ,857.3,861.3,864.1
XS GIS Cut Line= 4
     1514458.759      280850.625      1514311.19      281076.319
     1514293.829      281271.632     1514224.384      281822.847
#Sta/Elev= 30
       0  772.87    28.9  785.63    48.2  796.98    57.8  801.91    67.4  804.73
    86.7  805.38   163.7  805.19   173.4  803.85     183  800.82   211.9  789.28
     260  766.14   279.5  758.08   299.1  751.24   308.9  746.36  321.92736.5353
   328.5  731.56   338.3   727.6   348.1  727.88   406.9  742.87   416.7  746.14
   436.3  754.82   465.7  770.45   485.2  779.85   504.7  786.63     534  793.33
     573   796.8   641.2  800.64   806.9  802.98   953.1  816.34  1021.3  825.18
#Mann= 3 , 0 , 0
       0     .06       0  321.92    .045       0   348.1      .1       0
Bank Sta=321.92,348.1
XS Rating Curve= 0 ,0
Exp/Cntr=0.3,0.1

Type RM Length L Ch R = 1 ,29745.6 ,489.8,510.3,530.4
XS GIS Cut Line= 4
     1513707.891      281006.875     1513655.808      281479.965
     1513616.745      281657.916     1513573.343      281979.097
#Sta/Elev= 30
       0  798.09   126.3  793.68   184.6  787.22   213.7  787.52   223.4  786.71
   242.8  782.36   291.4  767.85   359.4  751.55     408  737.92   485.5  727.53
   514.3  724.68   533.5  721.14   543.1  719.24   552.7  719.09     556  719.59
   581.4  724.46     591  727.45   600.6  732.18   619.8     745     639  759.27
   677.8  793.29   697.4  808.44   746.5  842.47   756.4  848.35   766.2  852.58
   785.8  856.87   844.7  859.76   923.3  853.13     943  855.81   982.2  866.21
#Mann= 3 , 0 , 0
       0      .1       0   533.5    .045       0     556      .1       0
Bank Sta=533.5,556
XS Rating Curve= 0 ,0
Exp/Cntr=0.3,0.1

Type RM Length L Ch R = 1 ,29235.3 ,544.1,573.9,601.6
XS GIS Cut Line= 4
     1513677.509      280898.368     1513473.516       281093.68
     1513269.523      281193.507     1512857.197      281388.819
#Sta/Elev= 30
       0  795.12    29.2  792.48    87.6  785.98   107.1  781.99   155.8  766.64
   214.2  743.85   233.7  737.06   243.5  734.67   253.2  733.37   348.7  727.59
   367.6  724.77   386.5  720.74     396  719.14   405.4  719.03   414.9   721.3
   417.3  722.49   424.4  726.03   433.8  731.62   481.1  753.46   500.1   763.5
   596.9   825.7     694  886.05   839.6  981.42   888.1 1015.23   897.8 1020.31
   907.5 1023.25   917.2 1024.58   936.6    1026   946.4 1026.03   965.8 1024.46
#Mann= 3 , 0 , 0
       0      .1       0   386.5    .045       0   417.3      .1       0
Bank Sta=386.5,417.3
XS Rating Curve= 0 ,0
Exp/Cntr=0.3,0.1

Type RM Length L Ch R = 1 ,28661.3 ,186.6,187,187.4
XS GIS Cut Line= 4
     1513759.974      280828.923     1513443.134      280650.972
     1513325.947      280533.784     1512957.023      280386.215
#Sta/Elev= 30
       0  796.52    29.5  794.57    49.1  792.44    68.8  788.29   127.7  773.53
   147.3  767.96   206.2  745.14   225.9  739.34   245.5  736.05   294.6   730.2
   333.9  726.86   382.9   724.4   421.9  718.48   431.6  718.19   441.4  720.28
  445.15722.2285   451.1  725.32   460.9  732.23   499.9  761.38   529.1  782.05
   558.2  800.41     597  826.57   674.5  882.86   693.9  895.73   790.8  951.72
   848.9  982.25   868.3  991.02   887.7  998.06   907.1 1003.84   926.5 1008.11
#Mann= 3 , 0 , 0
       0     .08       0   421.9    .045       0  445.15      .1       0
Bank Sta=421.9,445.15
XS Rating Curve= 0 ,0
Exp/Cntr=0.3,0.1

Type RM Length L Ch R = 1 ,28474.3 ,260.3,259.5,258.5
XS GIS Cut Line= 4
     1513833.759      280733.437     1513573.343      280525.104
     1513460.495      280407.916     1513113.273      280247.326
#Sta/Elev= 30
       0  790.92    39.2  785.44    68.7  778.88    78.5  777.37   117.7  773.82
   137.3  771.32   196.2  760.78   264.8   747.1   294.3  739.63   313.9  732.66
   333.5  724.13   352.6  718.95   371.8  717.42   381.4   718.2   390.9  721.28
   400.5  726.27   410.1  732.21   419.6   739.1   457.9  770.87   486.6  796.23
   496.2  803.02     555  830.18   633.5  860.76   672.8  873.94   702.2  882.74
   741.4  895.58   770.8  903.25   839.5  919.58   859.1  924.89   878.7  931.33
#Mann= 3 , 0 , 0
       0     .07       0   352.6    .045       0   381.4      .1       0
Bank Sta=352.6,381.4
XS Rating Curve= 0 ,0
Exp/Cntr=0.3,0.1

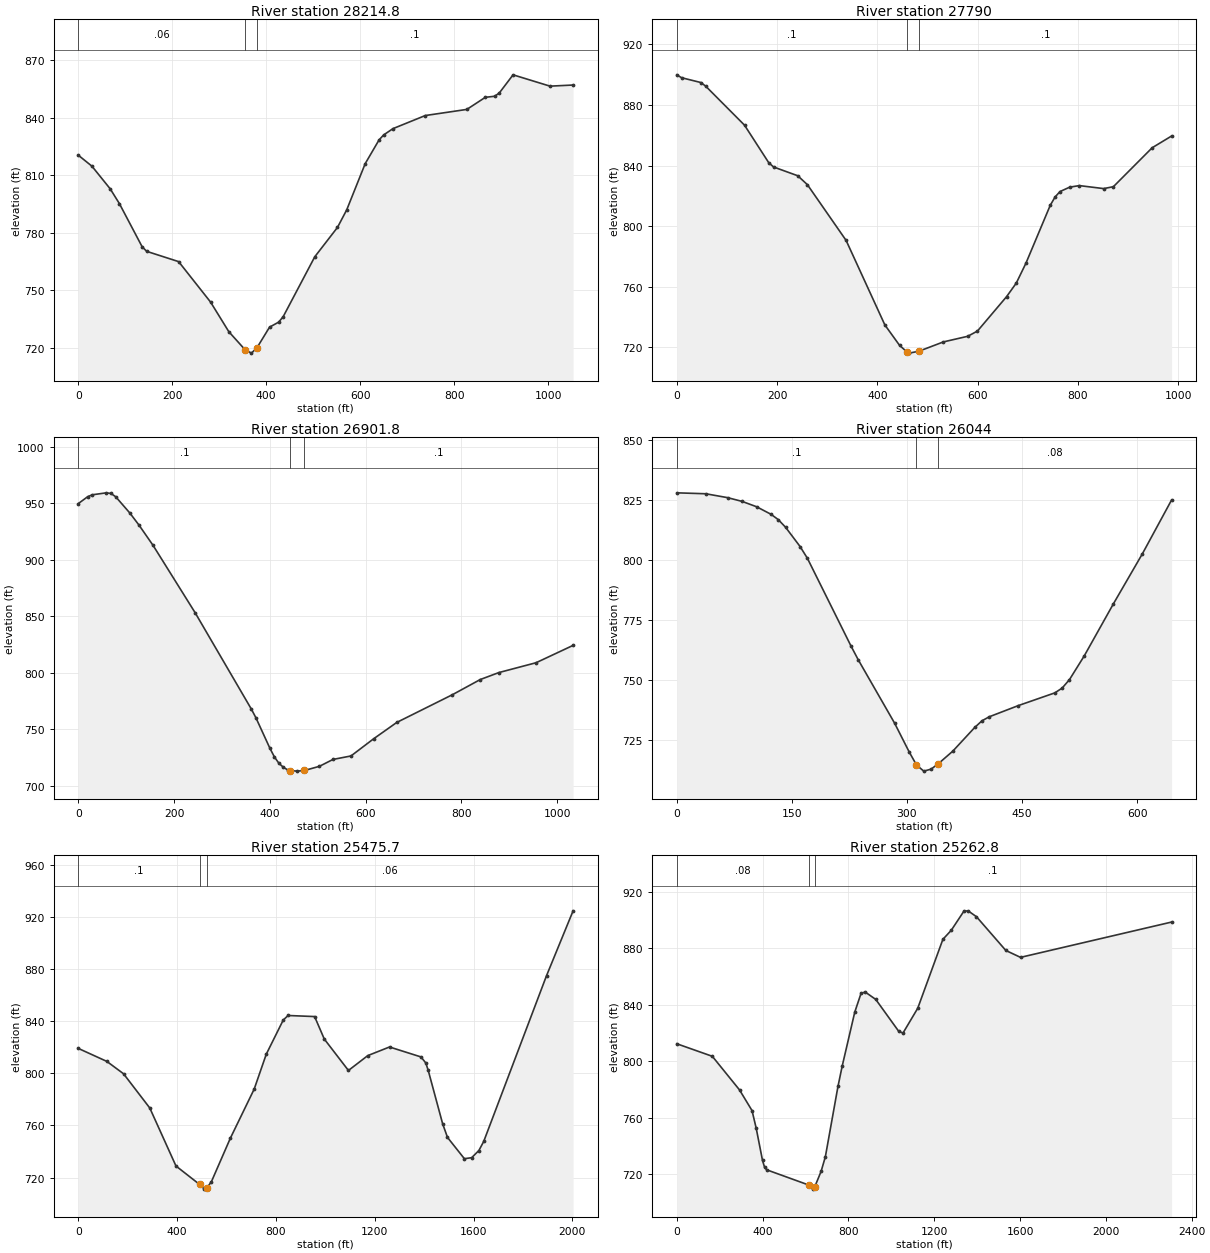
Type RM Length L Ch R = 1 ,28214.8 ,444.9,424.8,404.9
XS GIS Cut Line= 4
     1514085.495      280542.465     1513794.697      280386.215
     1513642.787      280238.646     1513234.801      279930.486
#Sta/Elev= 30
       0  820.47    29.1  814.72      68   802.9    87.4  795.27   135.9  772.74
   145.6  770.34   213.6  764.98   281.6  743.88   320.4  728.46  355.19718.9985
   368.6  717.28  380.54 720.167   407.1  730.82   426.4  733.43     436  736.23
   503.4  767.52   551.7  782.82   571.4     792   610.7  816.07   640.2  828.44
   650.1  831.05   669.7   834.3   738.6  841.14     827  844.33   866.4  850.64
     886  851.18   895.9  852.83   925.4  862.36    1004  856.46  1053.2  857.04
#Mann= 3 , 0 , 0
       0     .06       0  355.19    .045       0  380.54      .1       0
Bank Sta=355.19,380.54
XS Rating Curve= 0 ,0
Exp/Cntr=0.3,0.1

Type RM Length L Ch R = 1 ,27790   ,904.9,888.1,870.7
XS GIS Cut Line= 4
     1514328.551      280025.972     1513933.586      280004.271
     1513720.912      280025.972     1513360.669      279913.125
#Sta/Elev= 30
       0  899.93     9.6  898.02    48.2  894.83    57.9  892.37   135.1  866.68
   183.3  841.94     193  839.06   241.2  833.27   260.5  827.37   337.7  790.55
     415  734.71   444.2  721.28  459.41716.7565   463.6   716.1     483  717.37
   531.6   723.5   580.2  727.22   599.6  730.67   657.7   753.4   677.1  762.38
   696.5  775.64   744.8  813.75   754.5  819.26   764.2  822.82   783.6  825.74
   802.9  826.76   851.3  824.78   870.7  826.04   948.1  851.77   986.8  859.52
#Mann= 3 , 0 , 0
       0      .1       0  459.41    .045       0     483      .1       0
Bank Sta=459.41,483
XS Rating Curve= 0 ,0
Exp/Cntr=0.3,0.1

Type RM Length L Ch R = 1 ,26901.8 ,877.2,857.9,838.3
XS GIS Cut Line= 4
     1514020.391      278858.437     1513716.572      279118.854
     1513586.363      279279.444     1513351.988      279635.347
#Sta/Elev= 30
       0  949.55    19.5  955.63    29.3  957.36    58.6  959.09    68.3  958.52
    78.1  955.62   107.4  941.35   126.9  930.46   156.2  912.55     244  852.99
   361.1  767.92   370.9  760.05   400.2  732.97   409.6  725.34     419  719.76
   428.4  716.21   437.7  713.87  442.86713.4473   456.5   712.9   472.2  713.46
   503.5  717.18   531.7  723.24   569.3  726.32   616.6  741.52     665  756.01
   781.2  780.54   839.3  793.95   878.1   800.1   955.6  808.78    1033  824.15
#Mann= 3 , 0 , 0
       0      .1       0  442.86    .045       0   472.2      .1       0
Bank Sta=442.86,472.2
XS Rating Curve= 0 ,0
Exp/Cntr=0.3,0.1

Type RM Length L Ch R = 1 ,26044   ,554.3,568.3,582
XS GIS Cut Line= 4
     1512844.176      279027.708     1512874.558       279214.34
      1512913.62      279409.652     1512996.086      279652.708
#Sta/Elev= 30
       0  827.92    37.8  827.53    66.2  825.91    85.1  824.35     104  822.12
   122.9  818.96   132.4  816.71   141.8  813.56   160.7  805.53   170.2  800.65
     227  764.08   236.5   758.3   283.9  731.87   302.9  719.87   312.4  714.45
   321.9  711.87   331.4  712.69   340.8  714.94   359.8  720.22   388.3  730.07
   397.8  732.87   407.3  734.54   445.3  739.22   492.8  744.51   502.3  746.52
   511.8  750.03   530.9  759.84   568.9  781.55   606.9  802.54   644.9  824.95
#Mann= 3 , 0 , 0
       0      .1       0   312.4    .045       0   340.8     .08       0
Bank Sta=312.4,340.8
XS Rating Curve= 0 ,0
Exp/Cntr=0.3,0.1

Type RM Length L Ch R = 1 ,25475.7 ,201,213,225
XS GIS Cut Line= 4
     1512687.926      279032.048     1512405.808      279322.847
     1512292.961      279565.902     1511724.384      280768.159
#Sta/Elev= 30
       0  819.04   115.8  809.05   183.3  799.57   289.4  773.36   395.5  728.88
   491.3   714.7   510.4  711.15     520  711.92   539.2  716.98   615.7  750.24
   712.2  787.89   761.1  814.64   829.6  840.74   849.2  844.26   956.7  843.44
   995.8  826.22  1093.6  802.12  1171.9  813.51  1259.9  820.12    1387  812.51
  1406.6  807.92  1416.3  802.39    1475  761.22  1494.6  750.79    1563  734.47
  1592.4  735.25  1621.7  740.76  1641.2  747.68  1895.5  874.78  2003.1   924.5
#Mann= 3 , 0 , 0
       0      .1       0   491.3    .045       0     520     .06       0
Bank Sta=491.3,520
XS Rating Curve= 0 ,0
Exp/Cntr=0.3,0.1

Type RM Length L Ch R = 1 ,25262.8 ,823,848.4,873.6
XS GIS Cut Line= 4
     1512653.204       278906.18     1512236.537      279288.125
     1511993.481      279453.055     1510869.349      280364.514
#Sta/Elev= 30
       0  812.33   165.7  803.43   292.4  779.62   350.8  764.94   370.3  752.36
   399.6  729.62   409.3  724.74     419  722.98   614.2  712.23   633.8  709.28
   643.6  711.09   672.9  721.96   692.5  732.21   751.3  782.07   770.8  796.39
   829.6  834.78     859  848.12   878.5  848.97   927.4  843.75    1035  821.03
  1054.5  819.96    1123  837.49  1240.3  886.36  1279.4  892.78  1338.1   906.3
  1357.7  906.56  1396.8  902.38  1533.7  878.45  1602.1  873.57  2306.2   898.6
#Mann= 3 , 0 , 0
       0     .08       0   614.2    .045       0   643.6      .1       0
Bank Sta=614.2,643.6
XS Rating Curve= 0 ,0
Exp/Cntr=0.3,0.1

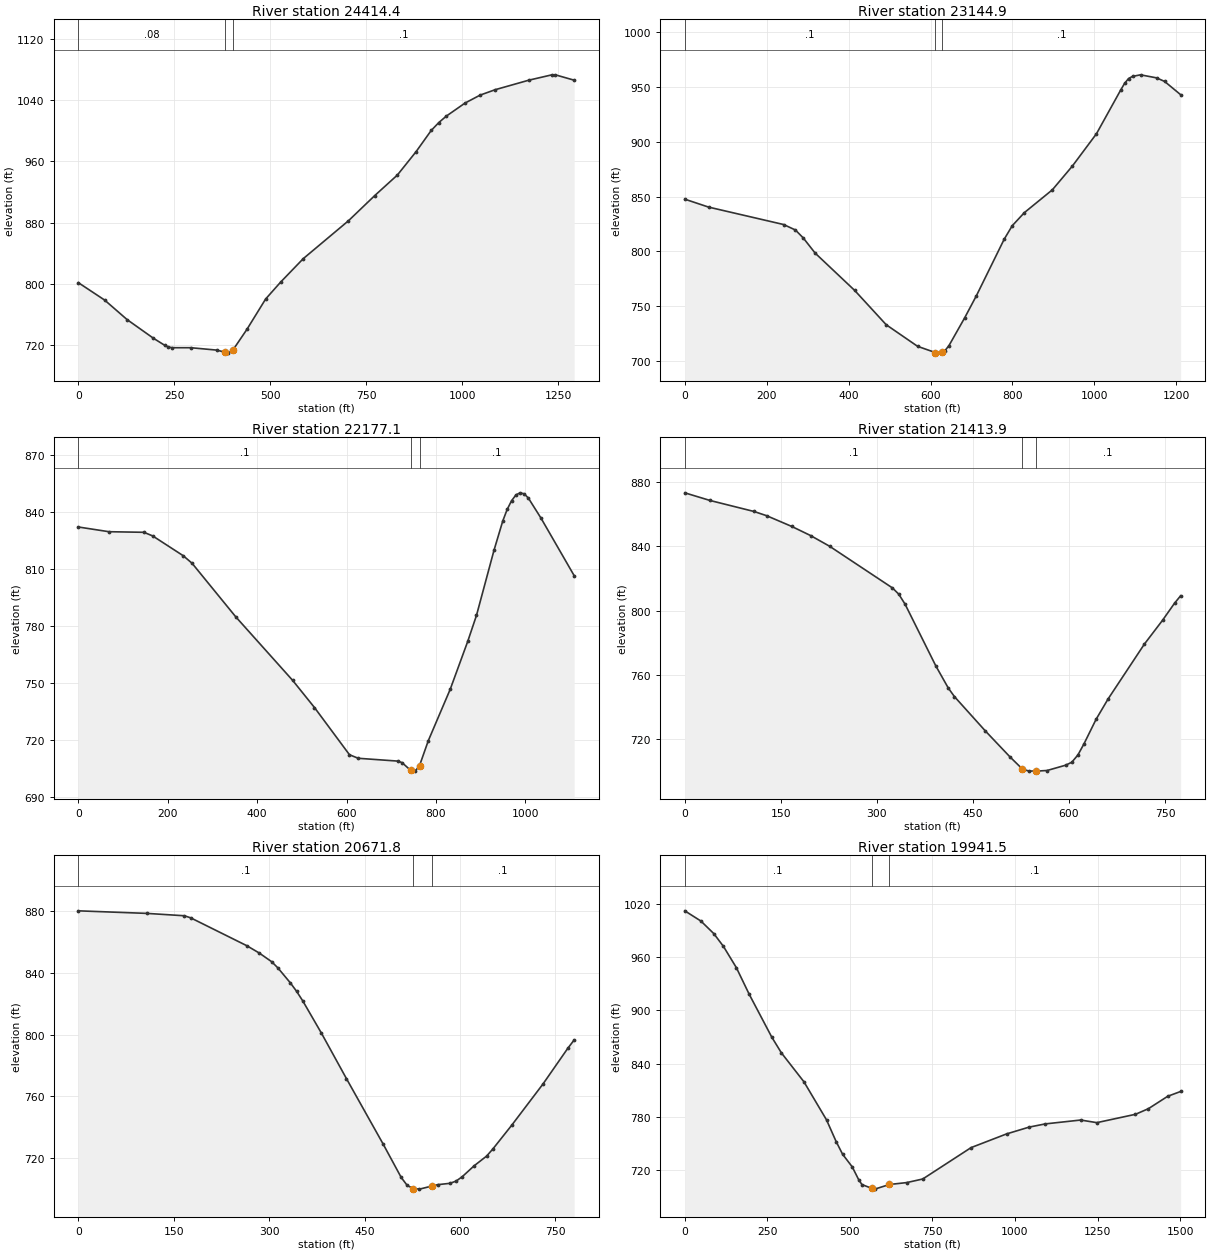
Type RM Length L Ch R = 1 ,24414.4 ,1266,1269.5,1272.2
XS GIS Cut Line= 4
     1512696.606      278754.271     1512388.447         278585.
     1512271.259      278515.555     1511468.308      278485.173
#Sta/Elev= 30
       0  801.21    68.4  778.45     127  752.85   195.3   728.5   224.6  719.28
   234.4  716.96   244.2  716.02     293  716.01   361.3  712.84   380.8  710.23
   390.5  708.92   402.1  712.61   439.2  740.15   487.8   779.8     527  802.02
   585.8  832.67   703.4  882.23     772  915.29   830.8  942.11   879.8  972.91
     919 1000.54   938.6  1010.8   958.2  1019.3  1007.2 1036.47  1046.4 1046.86
  1085.6 1053.94  1173.7 1066.48  1232.5 1073.33  1242.3 1073.43  1291.3 1066.41
#Mann= 3 , 0 , 0
       0     .08       0   380.8    .045       0   402.1      .1       0
Bank Sta=380.8,402.1
XS Rating Curve= 0 ,0
Exp/Cntr=0.3,0.1

Type RM Length L Ch R = 1 ,23144.9 ,940.2,967.8,994.5
XS GIS Cut Line= 4
     1513291.224       277964.34     1512939.662      277677.882
     1512713.968       277499.93     1512297.301      277282.916
#Sta/Elev= 30
       0  847.62    57.9  840.39   241.2  824.45   270.2  819.42   289.5  812.06
   318.4  798.27   414.9  764.17   491.8  732.83   568.5  713.08   611.8  707.42
   625.9  706.88  628.43707.5066   635.5  709.27   645.1   713.8   683.4  739.15
   712.2  759.49     780   811.1   799.6  823.38     829  835.27   897.5  856.17
   946.4   877.9  1005.2  907.43  1063.9  947.08  1073.7  953.37  1083.5  957.88
  1093.2  959.87  1112.8  961.29    1152  958.51  1171.6  955.25  1210.7  943.13
#Mann= 3 , 0 , 0
       0      .1       0   611.8    .045       0  628.43      .1       0
Bank Sta=611.8,628.43
XS Rating Curve= 0 ,0
Exp/Cntr=0.3,0.1

Type RM Length L Ch R = 1 ,22177.1 ,749.7,763.1,775.2
XS GIS Cut Line= 4
     1513334.627      277764.687     1513469.176      277213.472
     1513569.002      276814.166     1513634.106      276701.319
#Sta/Elev= 30
       0  832.18    68.5  829.69   146.7  829.38   166.3  827.48   234.8  817.02
   254.4  813.08   352.2  784.84   479.4  751.38   528.3  737.06   606.6  712.18
   626.2  710.31   714.4  708.83   724.2  708.03   743.8  703.89   753.6  703.54
   763.4  706.46     783  719.59     832  746.66   871.2   771.9   890.8  785.62
     930  819.94   949.6  835.36   959.4  841.42   969.2  845.99     979  849.06
   988.3  850.18   997.6  849.64  1006.9   847.4  1034.8  836.97  1109.3  806.55
#Mann= 3 , 0 , 0
       0      .1       0   743.8    .045       0   763.4      .1       0
Bank Sta=743.8,763.4
XS Rating Curve= 0 ,0
Exp/Cntr=0.3,0.1

Type RM Length L Ch R = 1 ,21413.9 ,754.1,742.2,729.6
XS GIS Cut Line= 4
     1513427.729      278088.549     1513662.104      277836.813
     1513853.077      277645.841     1513959.627      277525.972
#Sta/Elev= 30
       0  873.37    39.3  868.62   108.1  861.75   127.8  859.12   167.1  852.42
   196.5  846.74     226  840.13   324.3  814.13   334.1  810.27     344  804.04
   392.2  765.44   411.5  751.78   421.1  746.44   469.3  725.08   507.9  708.86
   527.2  701.33   536.9  700.09   546.5     700   548.2     700   565.8  700.39
   594.7  703.68   604.4  705.53     614  710.08   623.5  717.02   642.3  732.24
   661.2  745.02   717.8  779.14   746.1  793.94     765  804.66   774.4  809.24
#Mann= 3 , 0 , 0
       0      .1       0   527.2    .045       0   548.2      .1       0
Bank Sta=527.2,548.2
XS Rating Curve= 0 ,0
Exp/Cntr=0.3,0.1

Type RM Length L Ch R = 1 ,20671.8 ,751.6,730.2,705.9
XS GIS Cut Line= 4
     1514215.704      278628.402     1514337.231      278224.757
     1514389.315      278020.764     1514389.315      277873.194
#Sta/Elev= 30
       0   880.1   107.8  878.44   166.7  876.91   176.5   875.6   264.7  857.58
   284.3  852.84   303.9  847.21   313.7  843.21   333.3  833.53   343.1  828.08
   352.9  821.82   382.3  800.92   421.5   771.6     479  729.41   507.7  707.59
   517.2  702.41   526.8  700.38   536.4  700.06   555.5  702.01   565.1  702.95
   584.2  703.81   593.8  705.23   603.4  708.02   622.5  715.21   641.9  721.42
   651.8  726.05   681.3  741.33   730.5  768.02   769.8  791.28   779.6  796.56
#Mann= 3 , 0 , 0
       0      .1       0   526.8    .045       0   555.5      .1       0
Bank Sta=526.8,555.5
XS Rating Curve= 0 ,0
Exp/Cntr=0.3,0.1

Type RM Length L Ch R = 1 ,19941.5 ,1311,1290.3,1267.3
XS GIS Cut Line= 4
     1515535.148      278472.152     1515105.461      278150.972
     1514979.593      278016.423     1514237.405      277773.368
#Sta/Elev= 30
       0 1012.08    48.8 1000.56    87.8  986.42     117  972.01   156.1  948.09
   195.1     918   263.4  869.74   292.6  851.97   360.9  819.35   429.2  776.49
   458.4     752   477.9  737.75   507.2  723.44   526.7  708.99   536.5  703.55
   565.6   699.4   575.2  698.41   619.8  703.63   672.2  705.79   720.7  709.83
   867.1  745.21   974.5  760.63  1042.8   768.3  1091.7  771.92    1199  776.29
  1247.9  773.34    1365  782.75    1404  789.05  1462.6  803.06  1501.7  808.47
#Mann= 3 , 0 , 0
       0      .1       0   565.6    .045       0   619.8      .1       0
Bank Sta=565.6,619.8
XS Rating Curve= 0 ,0
Exp/Cntr=0.3,0.1

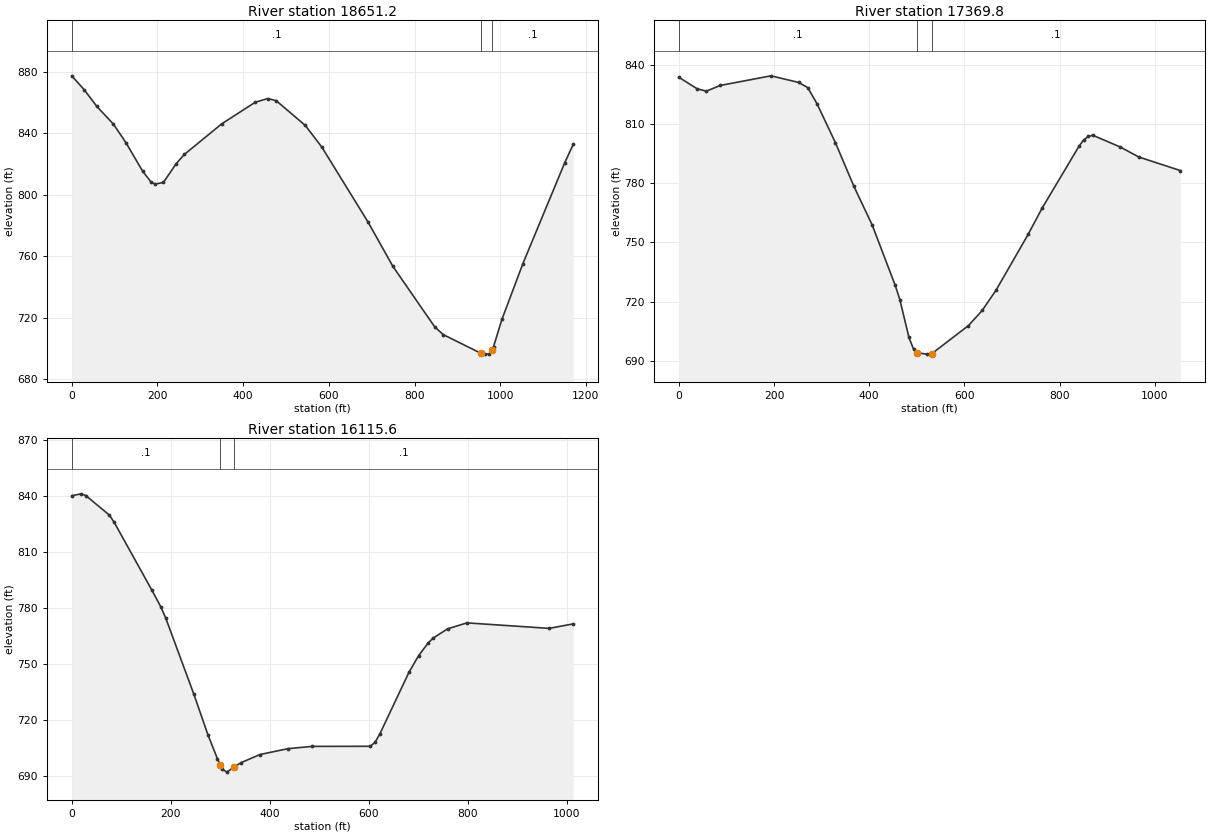
Type RM Length L Ch R = 1 ,18651.2 ,1289.6,1281.4,1272.6
XS GIS Cut Line= 3
     1515157.544      277213.472     1514454.419      277369.722
      1514007.37      277421.805
#Sta/Elev= 30
       0  877.19    29.2  868.12    58.4  857.37    97.3  845.81   126.5  833.78
   165.5   815.2   184.9  808.27   194.7  806.82   214.1  807.95   243.3  819.96
   262.8  826.12   350.4  846.06   428.3  860.02   457.5  862.42   476.9   861.1
   545.1  844.97     584  830.75   691.1  782.38   749.6  753.36   847.5  713.93
     867  709.05   955.1   696.9   964.9  696.36   974.7  696.47   980.4  699.23
   984.4  701.16    1004  718.95  1052.9  755.12  1150.8  820.86  1170.4  832.63
#Mann= 3 , 0 , 0
       0      .1       0   955.1    .045       0   980.4      .1       0
Bank Sta=955.1,980.4
XS Rating Curve= 0 ,0
Exp/Cntr=0.3,0.1

Type RM Length L Ch R = 1 ,17369.8 ,1271.6,1254.1,1235.8
XS GIS Cut Line= 4
     1514905.808      276037.257     1514480.461      276197.847
     1514285.148      276302.014     1514029.072      276579.791
#Sta/Elev= 30
       0  833.55    38.7  827.68      58  826.54    87.1  829.42   193.5  834.28
   251.5  830.95   270.9  828.31   290.2   820.2   328.9   800.5   367.6   778.5
   406.3  758.78   454.6  728.32   464.3  721.13   483.5  701.93   493.2     696
  501.02694.1835   520.7   693.5   531.6  693.76   608.6  707.95   637.5  715.61
   666.4   725.8   734.1  754.14   763.2  767.29   840.7  798.62   850.4  801.78
   860.1  803.59   869.8  804.22   927.9  798.23   966.6   793.2  1053.8  786.36
#Mann= 3 , 0 , 0
       0      .1       0  501.02    .045       0   531.6      .1       0
Bank Sta=501.02,531.6
XS Rating Curve= 0 ,0
Exp/Cntr=0.3,0.1

Type RM Length L Ch R = 1 ,16115.6 ,1470.3,1497,1521.9
XS GIS Cut Line= 4
     1513790.356       274999.93     1513716.572      275195.243
     1513660.148      275416.597     1513443.134      275950.451
#Sta/Elev= 30
       0  839.93      19  840.97    28.5  840.05    75.9  829.58    85.4  825.88
   161.3  789.67   180.3   780.3   189.8  774.52   246.9  733.54   275.4  711.77
   294.4  699.07  300.25695.7062     304  693.55   313.5  691.87  327.41694.4402
     342  696.91   380.1  701.28   437.2  704.45     486  705.66   603.3  705.71
     613  707.84   622.8  712.41   681.4  745.29   700.9  754.21   720.5  761.12
   730.2  763.64   759.5  768.61   798.6  771.83   964.7  768.89  1013.5  771.29
#Mann= 3 , 0 , 0
       0      .1       0  300.25    .045       0  327.41      .1       0
Bank Sta=300.25,327.41
XS Rating Curve= 0 ,0
Exp/Cntr=0.3,0.1