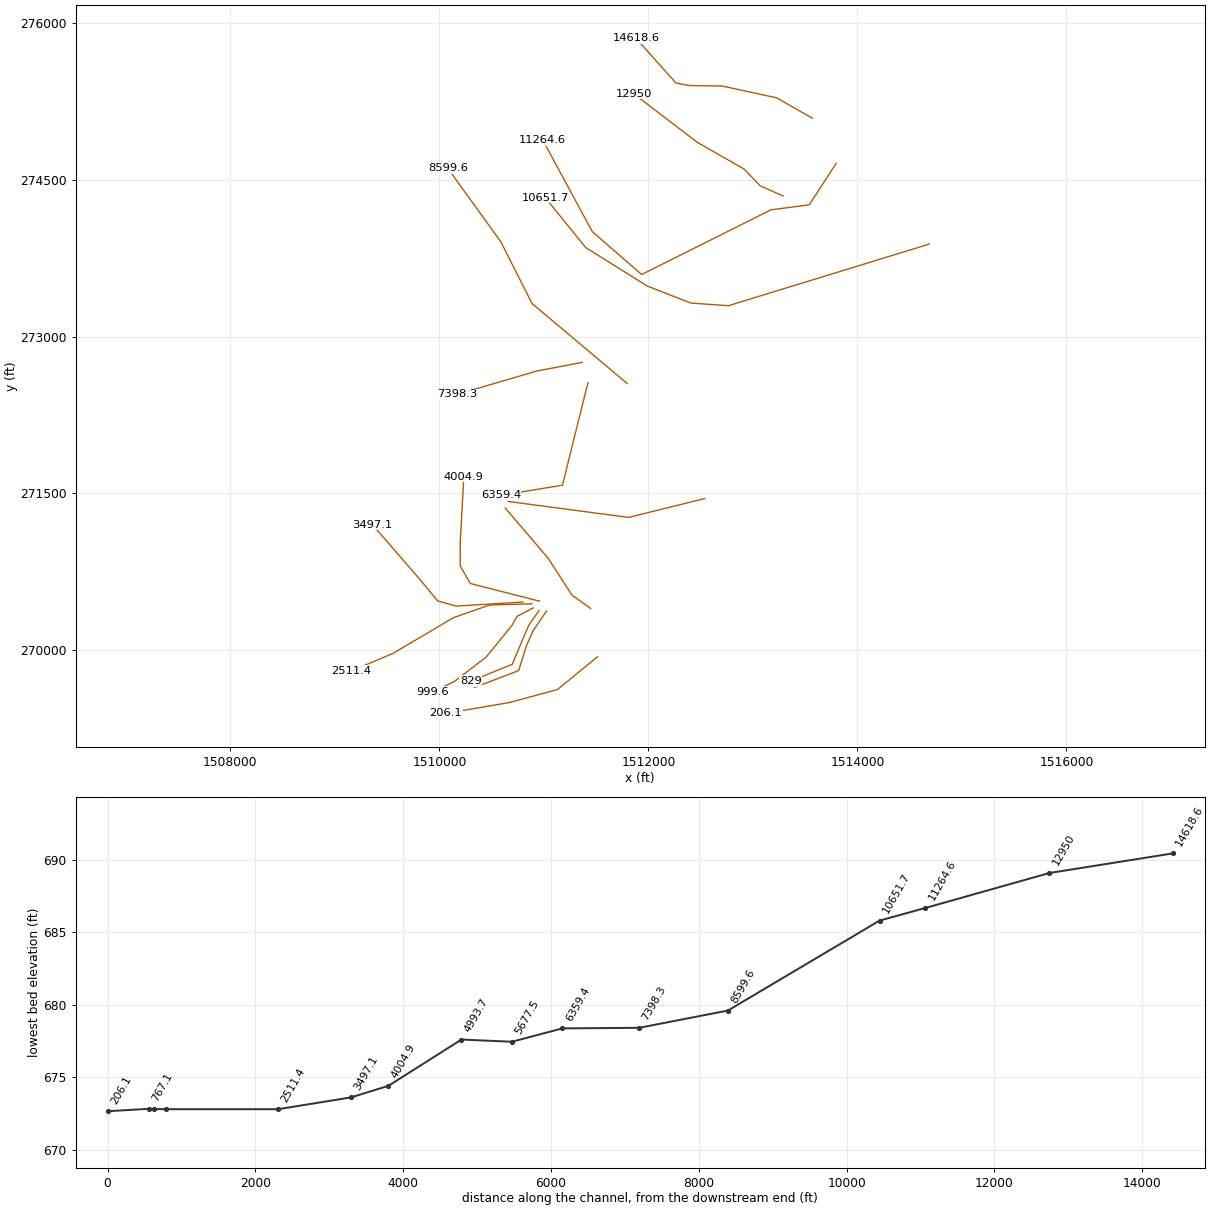
HEC-RAS study BNDSCR.prj: BNDSCR

--- BNDSCR.g01 (geometry) --- (continued)

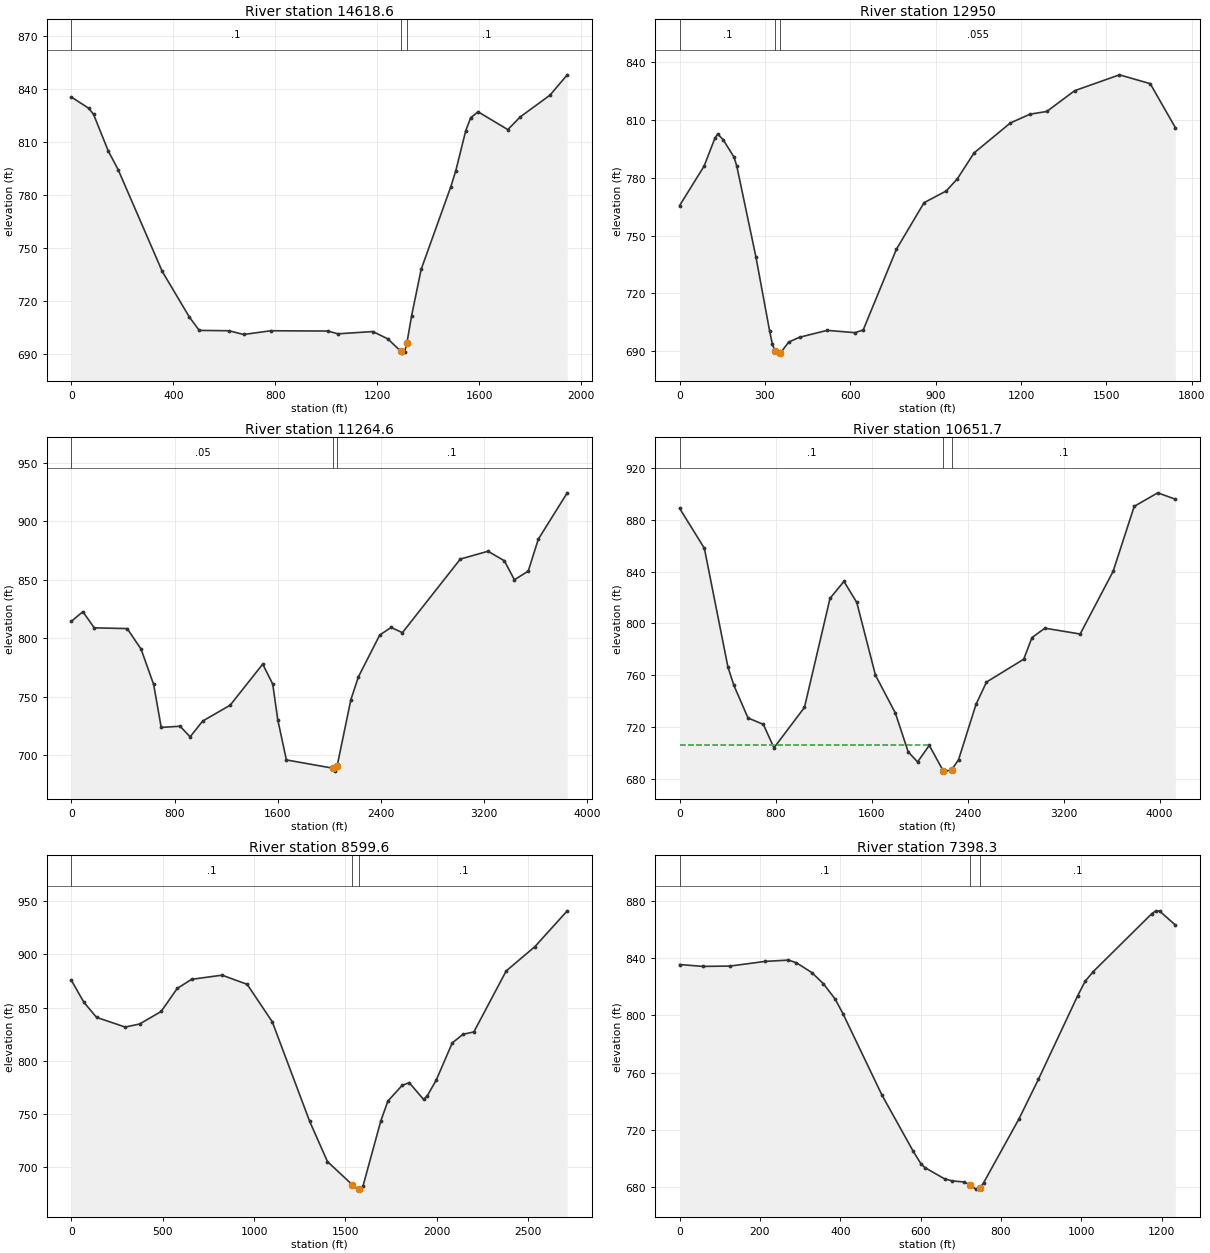
Type RM Length L Ch R = 1 ,14618.6 ,1682.4,1668.6,1654.2
XS GIS Cut Line= 6
     1513569.002      275086.736      1513226.12      275282.048
     1512705.287      275394.896     1512391.919      275399.236
     1512263.447      275423.541     1511881.502      275850.625
#Sta/Elev= 30
       0  835.62    67.4  829.31    86.6  825.88   144.4  805.03   182.9  794.55
   356.1  736.76   462.4  710.91   501.2  703.32   617.5  703.12   675.6  701.01
   782.2  703.12  1005.9  702.95    1045  701.38  1182.2  702.67  1240.9  698.51
 1291.55 691.509    1297  690.43  1306.3  691.02  1315.6  696.09  1334.3  711.73
  1371.7  737.98  1488.2  784.89  1507.6  793.93  1546.5  816.55  1565.9  823.93
    1595  827.25  1711.6  817.18  1760.1  824.37  1876.7  836.68  1944.6  848.24
#Mann= 3 , 0 , 0
       0      .1       0 1291.55    .045       0  1315.6      .1       0
Bank Sta=1291.55,1315.6
XS Rating Curve= 0 ,0
Exp/Cntr=0.3,0.1

Type RM Length L Ch R = 1 ,12950   ,1656.8,1685.4,1711.2
XS GIS Cut Line= 5
     1513287.752       274343.68     1513069.002      274440.902
     1512916.224      274600.625     1512467.976      274856.078
     1511858.788      275321.227
#Sta/Elev= 30
       0  765.51    86.2  785.97   124.5  800.56     134  802.59   153.2  799.67
   191.5  790.58   201.1  785.96   268.2  739.04   316.3  700.71   325.9     694
   335.5  690.03   345.1  689.08   354.7  689.17   383.5   694.8     422  697.31
   518.8  700.88   616.2  699.68   645.4  701.07   762.2  742.91   859.5  767.03
   937.4   773.1   976.3  779.38  1035.3  792.82    1163  808.34  1231.8  812.87
  1290.8  814.28    1389  825.06  1546.3  833.26  1654.4  828.68  1742.8  805.89
#Mann= 3 , 0 , 0
       0      .1       0   335.5    .045       0   354.7    .055       0
Bank Sta=335.5,354.7
XS Rating Curve= 0 ,0
Exp/Cntr=0.3,0.1

Type RM Length L Ch R = 1 ,11264.6 ,622.7,612.9,604.7
XS GIS Cut Line= 6
     1513796.433      274655.312     1513539.488      274259.479
     1513171.433      274210.868     1511935.322      273592.812
     1511463.099      274002.534     1510988.996      274878.518
#Sta/Elev= 30
       0  814.58    88.5  822.75     177  808.96   432.6  808.33   540.3  790.79
     638  760.61   696.6  723.98   843.2  724.96   920.9  715.92  1018.1  729.38
  1231.8  742.94  1484.5  778.01  1562.2  760.94  1601.1  730.56  1668.3  696.22
  2033.6  689.09  2043.3  686.66  2062.6  691.44  2168.7  747.66  2226.6  767.03
  2392.7  802.85  2480.6   809.3  2568.6  804.86  3017.8  867.65  3232.7  874.34
  3359.6  866.23  3437.8     850  3545.2  857.39  3623.3  884.64  3847.9   924.2
#Mann= 3 , 0 , 0
       0     .05       0  2033.6    .045       0  2062.6      .1       0
Bank Sta=2033.6,2062.6
XS Rating Curve= 0 ,0
Exp/Cntr=0.3,0.1

Type RM Length L Ch R = 1 ,10651.7 ,2074.8,2052.2,2025.1
XS GIS Cut Line= 6
     1514686.913      273883.727     1512765.906      273294.751
     1512405.663      273319.924     1511990.877      273481.701
     1511400.599      273849.757     1511011.711      274328.923
#Sta/Elev= 30
       0  888.88   206.5  857.98   403.1  766.19   452.3  752.15   570.3  726.87
   698.1  721.92   786.6  703.81  1040.7  735.02  1253.7  819.29  1369.8  832.38
  1476.5  816.17  1632.5  759.91  1798.2  730.69  1905.4  700.64  1983.4  692.91
    2081  705.72  2198.1  685.83  2207.9   685.8  2266.4   686.7    2325  694.65
  2470.6  737.44  2557.7  754.61    2868  772.27  2936.6  788.97  3044.4  796.24
  3338.3  791.72  3612.6  840.06  3788.9  890.35  3984.8   900.8  4131.8  895.86
#Mann= 3 , 0 , 0
       0      .1       0  2198.1    .045       0  2266.4      .1       0
#XS Ineff= 2 , 0
         2081.62  705.96
Permanent Ineff=
       F       F
Bank Sta=2198.1,2266.4
XS Rating Curve= 0 ,0
Exp/Cntr=0.3,0.1

Type RM Length L Ch R = 1 ,8599.6  ,1169.3,1201.3,1231.9
XS GIS Cut Line= 4
     1511796.433      272551.146     1510886.711      273315.034
     1510588.099      273905.312     1510081.155      274606.701
#Sta/Elev= 30
       0  875.45    68.7  854.84   137.4  840.84   294.5  831.73   373.1  834.61
   490.9  846.34   579.2  867.99   657.8  876.54   824.7  880.44   962.1  871.85
  1099.6  836.69  1304.6  743.13  1401.9  705.43  1538.1  683.67  1567.3   679.6
    1577  679.62  1596.5  682.56  1693.8  743.53  1732.7  762.26  1810.5  776.92
  1849.4  779.55  1928.1  763.82  1947.8  767.05  1996.9  781.77  2085.4   816.9
  2144.4  824.97  2203.4  827.17  2380.5  884.42  2537.8  907.25  2714.8  940.84
#Mann= 3 , 0 , 0
       0      .1       0  1538.1    .045       0    1577      .1       0
Bank Sta=1538.1,1577
XS Rating Curve= 0 ,0
Exp/Cntr=0.3,0.1

Type RM Length L Ch R = 1 ,7398.3  ,1014.3,1038.9,1061.6
XS GIS Cut Line= 3
     1511365.877      272752.534     1510928.377      272669.201
     1510171.433      272446.979
#Sta/Elev= 30
       0  835.55    58.1  834.24   125.9  834.48     213  837.74   271.1  838.65
   290.5  836.83   329.2  829.94   358.2  822.07   387.3   811.4   406.6  801.26
   503.8  744.22   581.7  704.88   601.2  696.04   610.9  693.43   659.6  685.63
   679.1  684.14   708.3  683.43  723.21681.4032   737.6  678.41   747.3  679.04
     757  682.91   844.7  727.42   893.4  755.28   990.8  813.56  1010.2  824.03
  1029.7  830.56  1175.8  871.18  1185.6  873.12  1195.3  872.88  1234.3  863.18
#Mann= 3 , 0 , 0
       0      .1       0  723.21    .045       0   747.3      .1       0
Bank Sta=723.21,747.3
XS Rating Curve= 0 ,0
Exp/Cntr=0.3,0.1

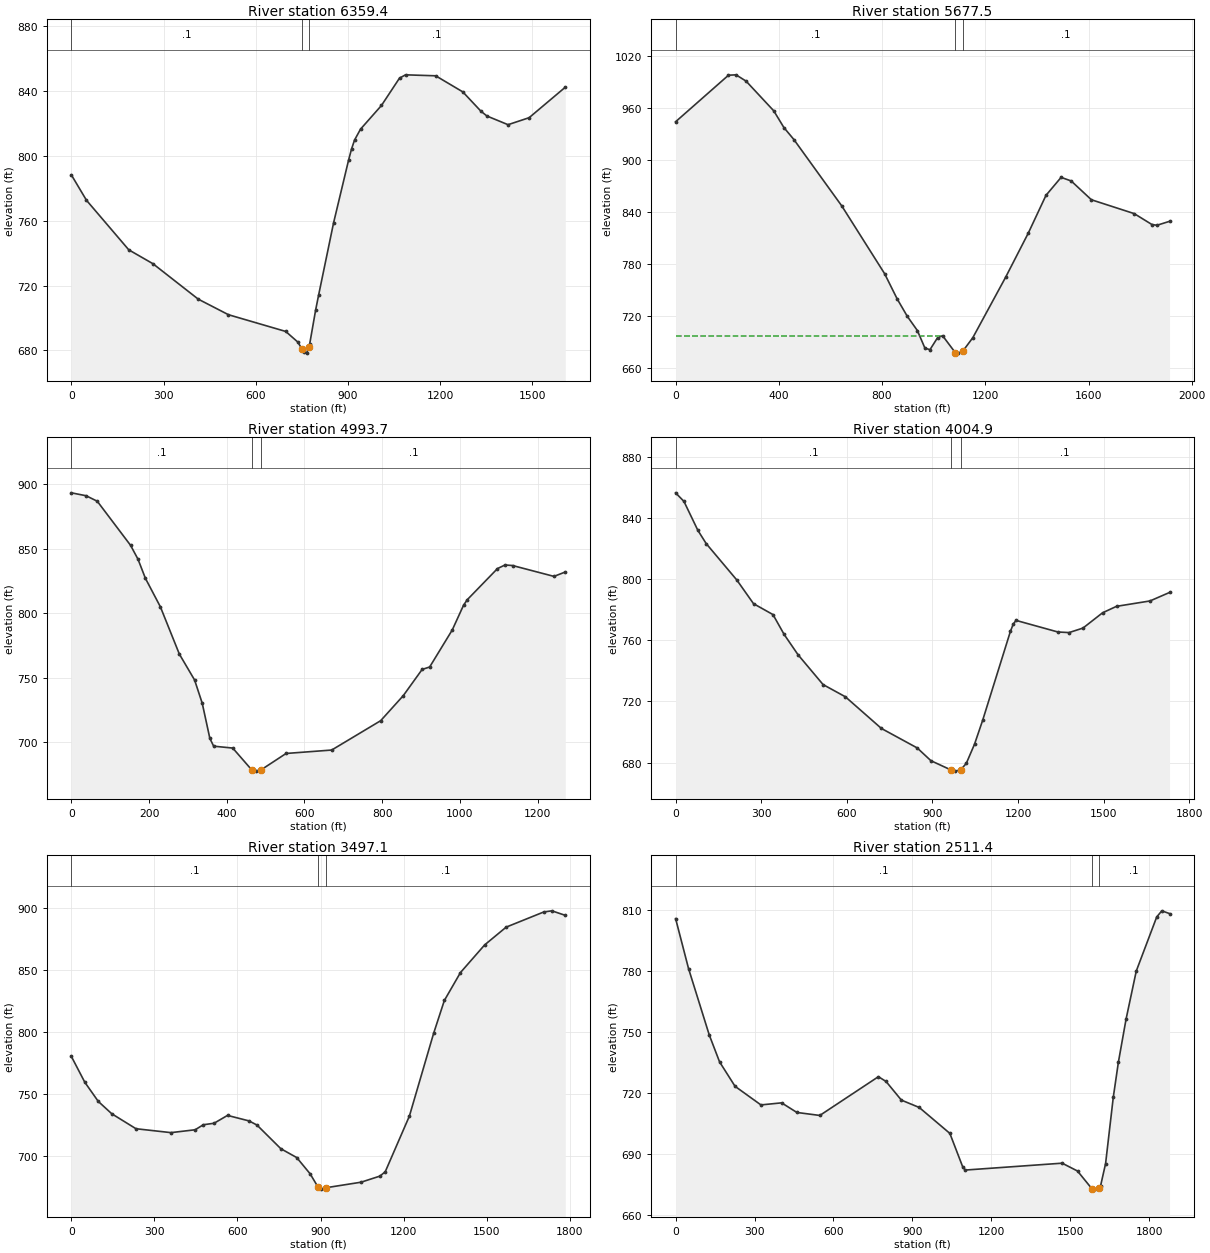
Type RM Length L Ch R = 1 ,6359.4  ,714.5,681.9,648
XS GIS Cut Line= 4
     1511421.433       272558.09     1511261.711      271919.201
     1511178.377      271578.923     1510588.099      271481.701
#Sta/Elev= 30
       0  788.19    49.2  772.55   186.8  742.02   265.4  733.47   412.8  711.64
   511.1  702.04   697.5  691.73   736.4  685.26  750.64680.8551   755.9  678.98
   765.6  678.37  772.12682.0331   775.3  683.82   794.8  704.91   804.5  714.13
   853.2  758.67   901.8  797.15   911.6  804.14   921.3  809.62   940.8  816.37
  1008.9  830.96  1067.7  847.83  1087.3  849.86  1185.4  849.26  1273.7  839.34
  1332.5  827.47  1352.1  824.49  1420.8  819.13  1489.4  823.44  1607.1  842.22
#Mann= 3 , 0 , 0
       0      .1       0  750.64    .045       0  772.12      .1       0
Bank Sta=750.64,772.12
XS Rating Curve= 0 ,0
Exp/Cntr=0.3,0.1

Type RM Length L Ch R = 1 ,5677.5  ,702.9,683.8,663.9
XS GIS Cut Line= 3
     1512539.488      271451.146     1511810.322       271270.59
     1510657.544      271423.368
#Sta/Elev= 30
       0  944.01   204.9  997.63   234.1  998.07   273.2  990.78   380.5  956.53
   419.5  937.38   458.5  923.45   643.9  847.04   809.8  769.03   858.7  739.83
   897.8  719.85   936.8  703.51   966.2  683.15   985.7  681.44    1015   695.2
  1034.6  697.51  1083.4  678.17  1093.2  677.45  1112.8  679.67  1151.8  695.29
  1278.9  764.91  1366.8  815.79  1435.2  859.22  1493.8  879.93  1532.9  875.81
  1611.1  854.15  1777.2  838.17  1845.6  825.63  1865.2  824.75    1914  829.28
#Mann= 3 , 0 , 0
       0      .1       0  1083.4    .045       0  1112.8      .1       0
#XS Ineff= 2 , 0
         1033.56  697.73
Permanent Ineff=
       F       F
Bank Sta=1083.4,1112.8
XS Rating Curve= 0 ,0
Exp/Cntr=0.3,0.1

Type RM Length L Ch R = 1 ,4993.7  ,1001.3,988.9,974.7
XS GIS Cut Line= 4
      1511447.33      270400.654     1511268.655      270527.534
     1511039.488      270881.701     1510629.766      271360.868
#Sta/Elev= 30
       0  893.34    38.1  891.07    66.7  886.81   152.4  852.64   171.5   841.9
   190.6  827.06     229  805.07     278  768.32   317.2  748.24   336.9   730.2
   356.5  702.96   366.3  696.94   415.4  695.48   464.4  678.53   474.2   677.6
  489.02678.7256   552.7  691.29   670.1  693.94   796.2   716.7   854.4  736.12
   902.9  756.43   922.3  758.33   980.5  787.05  1009.6  806.26  1019.3  810.55
  1096.8   834.6  1116.2  837.41  1135.6  836.99  1242.3  828.56  1271.4  831.97
#Mann= 3 , 0 , 0
       0      .1       0   464.4    .045       0  489.02      .1       0
Bank Sta=464.4,489.02
XS Rating Curve= 0 ,0
Exp/Cntr=0.3,0.1

Type RM Length L Ch R = 1 ,4004.9  ,490.8,507.8,522.9
XS GIS Cut Line= 5
     1510957.746      270470.098     1510296.433      270638.646
     1510199.211      270805.312     1510199.211      271034.479
     1510233.933      271659.479
#Sta/Elev= 30
       0  856.52    29.2  850.91      78  831.96   107.2  823.29   214.5  799.46
     273  783.98   341.2  776.84   380.2  763.87     429  750.55   516.7  731.04
   594.7  723.07     721  702.34   846.5  689.58   894.5  681.23  966.18675.0581
   980.4  674.41   999.5  675.37  1018.6  679.55  1047.3  692.06  1075.9  707.74
    1173  765.86  1182.8  770.57  1192.6  773.05  1339.3  765.46  1378.4  765.07
  1427.3  768.02  1495.8  778.01  1544.7  782.24  1662.1  785.77  1730.5  791.32
#Mann= 3 , 0 , 0
       0      .1       0  966.18    .045       0   999.5      .1       0
Bank Sta=966.18,999.5
XS Rating Curve= 0 ,0
Exp/Cntr=0.3,0.1

Type RM Length L Ch R = 1 ,3497.1  ,954.5,985.6,1015.1
XS GIS Cut Line= 5
      1510799.76      270461.418     1510159.135      270423.223
     1509983.933      270471.979     1509817.266      270673.368
     1509358.933      271201.146
#Sta/Elev= 30
       0  780.38    48.6   759.6    97.2   744.2   145.9  734.26   233.4  722.21
   359.8  719.07   447.3  721.38   476.5  725.41   515.4  726.62     564  732.93
   641.8   728.5   670.5  725.16   756.6  706.13     814  699.01   862.4  685.94
   891.4  675.07     901  673.61   920.4  674.76  1046.3  679.18  1114.2  684.07
  1133.6  687.55    1221  732.42  1308.3  798.86  1347.2  825.42  1405.4  847.88
  1492.8  870.13  1570.5  884.43  1706.4  896.64  1735.5  897.55    1784  893.92
#Mann= 3 , 0 , 0
       0      .1       0   891.4    .045       0   920.4      .1       0
Bank Sta=891.4,920.4
XS Rating Curve= 0 ,0
Exp/Cntr=0.3,0.1

Type RM Length L Ch R = 1 ,2511.4  ,1496.1,1511.8,1525.3
XS GIS Cut Line= 5
      1510884.83      270444.056     1510482.052       270433.64
      1510134.83      270312.112     1509558.441      269971.834
     1509155.663      269801.695
#Sta/Elev= 30
       0  805.93    49.1  781.37   127.8   748.7   167.1  735.42     226  723.39
   324.3  714.24   402.9  715.26     461  710.53   548.1  709.06   770.8  728.13
   799.9  725.78   858.1  716.61     926  712.99  1042.4  700.23  1090.9  683.88
  1100.6  682.18  1469.3  685.57  1527.6  681.71 1582.63672.9415  1595.6   672.8
  1608.7673.3632    1615  674.24  1634.4  685.41  1663.6  718.02    1683  735.26
  1712.2  756.47    1751  780.14  1828.8  806.78  1848.2  809.76  1877.4   808.4
#Mann= 3 , 0 , 0
       0      .1       0 1582.63    .045       0  1608.7      .1       0
Bank Sta=1582.63,1608.7
XS Rating Curve= 0 ,0
Exp/Cntr=0.3,0.1

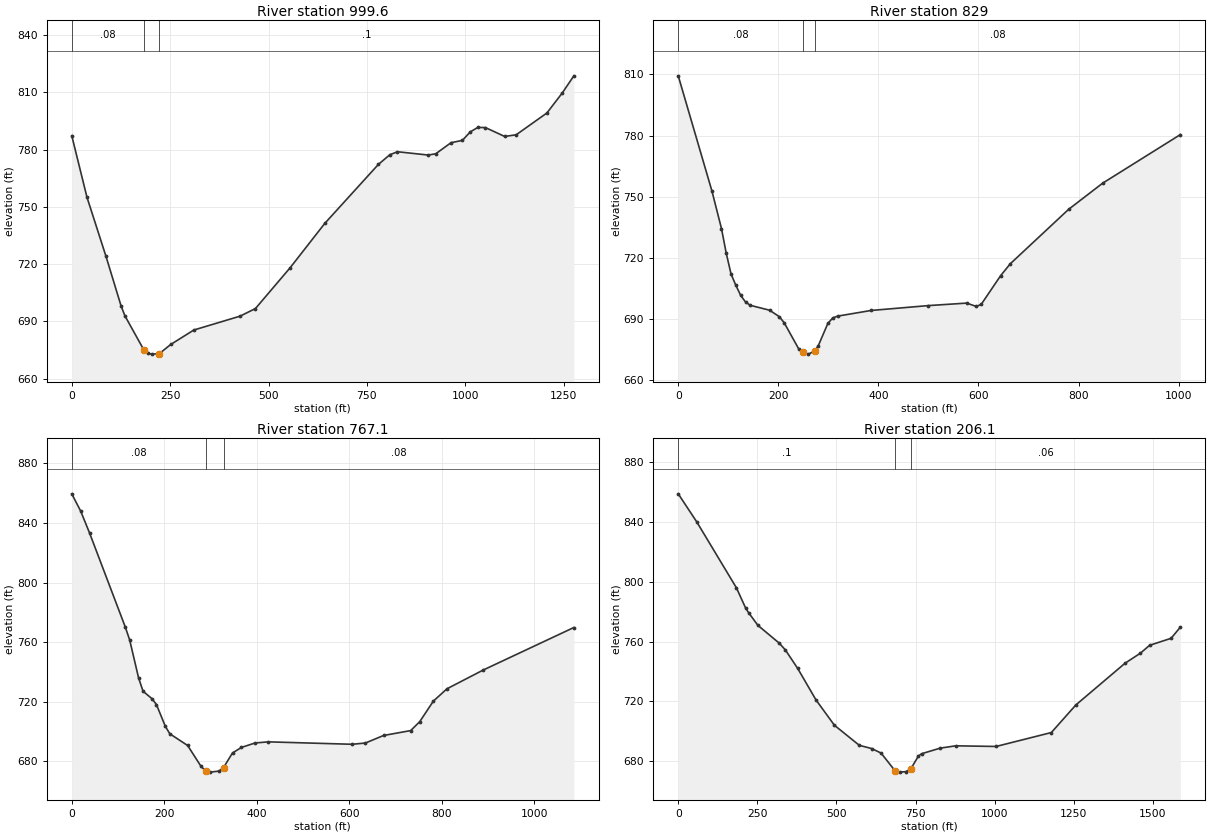
Type RM Length L Ch R = 1 ,999.6   ,167.6,170.6,172.8
XS GIS Cut Line= 6
     1510897.561      270405.139     1510743.481      270324.843
     1510695.738      270240.208     1510448.343      269936.389
     1510140.183      269699.843     1509936.913      269603.779
#Sta/Elev= 30
       0   787.3    38.6  755.08    86.9   724.1   125.5  697.96   135.1  692.87
   183.5   674.9   193.2  673.16   202.9   672.8   222.3  673.02   251.5  677.86
   310.1  685.43   427.6   692.7   466.8   696.7     555   718.1   643.1  741.36
   779.3  772.28   808.4  777.34   827.8  778.91   905.5  777.18     925  777.83
   963.8  783.64   992.9  784.88  1012.4  789.27  1031.8  791.64  1051.2  791.59
  1100.1  786.93  1129.4  787.79  1207.6  799.24  1246.7  809.76    1276  818.71
#Mann= 3 , 0 , 0
       0     .08       0   183.5    .045       0   222.3      .1       0
Bank Sta=183.5,222.3
XS Rating Curve= 0 ,0
Exp/Cntr=0.3,0.1

Type RM Length L Ch R = 1 ,829     ,61.7,61.9,62.2
XS GIS Cut Line= 5
     1510952.538       270379.82     1510858.788       270246.14
     1510792.816      270095.098      1510697.33      269865.931
     1510301.207      269706.354
#Sta/Elev= 30
       0  809.28    67.2  752.91    86.4  734.41      96  722.22   105.6  712.05
   115.2  706.53   124.9  701.57   134.5  698.36   144.1  696.74   182.7  694.33
   202.1  691.15   211.8  688.18   240.8  675.37  248.37673.6531   260.2  672.81
  272.56674.3749   279.6  676.77     299  687.85   308.7  690.53   318.4  691.44
   385.4  694.22     500  696.61   576.4  697.83   595.8  696.18   605.5  697.21
   644.3  711.28   663.7  717.14   780.2  743.81   848.1  756.62  1003.4  780.45
#Mann= 3 , 0 , 0
       0     .08       0  248.37    .045       0  272.56     .08       0
Bank Sta=248.37,272.56
XS Rating Curve= 0 ,0
Exp/Cntr=0.3,0.1

Type RM Length L Ch R = 1 ,767.1   ,581.1,561,539.9
XS GIS Cut Line= 5
     1511025.455      270376.348     1510895.246      270185.376
     1510829.274      270034.334     1510758.672       269806.18
     1510337.665       269645.59
#Sta/Elev= 30
       0  859.59    19.3  847.97    38.5  833.27   115.6  770.28   125.2   761.5
   144.5  735.98   154.1  727.12   173.4  722.12     183   718.2   202.2  703.64
   211.9  698.56   250.5  690.71   279.6  676.61   289.3  673.71     299  672.83
   318.4  673.52   328.1  675.92   347.5  685.71   366.9  689.42     396  692.37
   424.6  693.15   606.1  691.52   634.8  692.36     674  697.42   732.7  700.71
   752.3  706.72   781.7  720.48   811.1  728.76   889.5  741.35  1085.4  769.88
#Mann= 3 , 0 , 0
       0     .08       0   289.3    .045       0   328.1     .08       0
Bank Sta=289.3,328.1
XS Rating Curve= 0 ,0
Exp/Cntr=0.3,0.1

Type RM Length L Ch R = 1 ,206.1   ,221.1,206.1,191
XS GIS Cut Line= 4
     1511511.711      269937.257     1511129.766      269624.757
     1510664.488      269499.757     1510061.913      269397.181
#Sta/Elev= 30
       0  858.94    58.1   840.3   183.8  796.05   212.9  782.51   222.6  779.32
   251.6  770.93   319.3  758.96   338.7  754.41   377.4  742.09   435.4  720.96
   493.5  704.04   572.2   690.6   611.5  688.42     641   685.4  685.19673.5364
     700  672.66   719.6  672.99  734.41674.6873     759  683.42   768.8  684.96
   827.8  688.72     877  690.27  1004.4  689.84    1179  699.16  1256.6  717.66
  1411.9  745.56  1460.4  752.28  1489.5  757.54  1557.4  762.24  1586.5  769.66
#Mann= 3 , 0 , 0
       0      .1       0  685.19    .045       0  734.41     .06       0
Bank Sta=685.19,734.41
XS Rating Curve= 0 ,0
Exp/Cntr=0.3,0.1

Chan Stop Cuts=-1
Use User Specified Reach Order=0
Composite Channel Slope=5